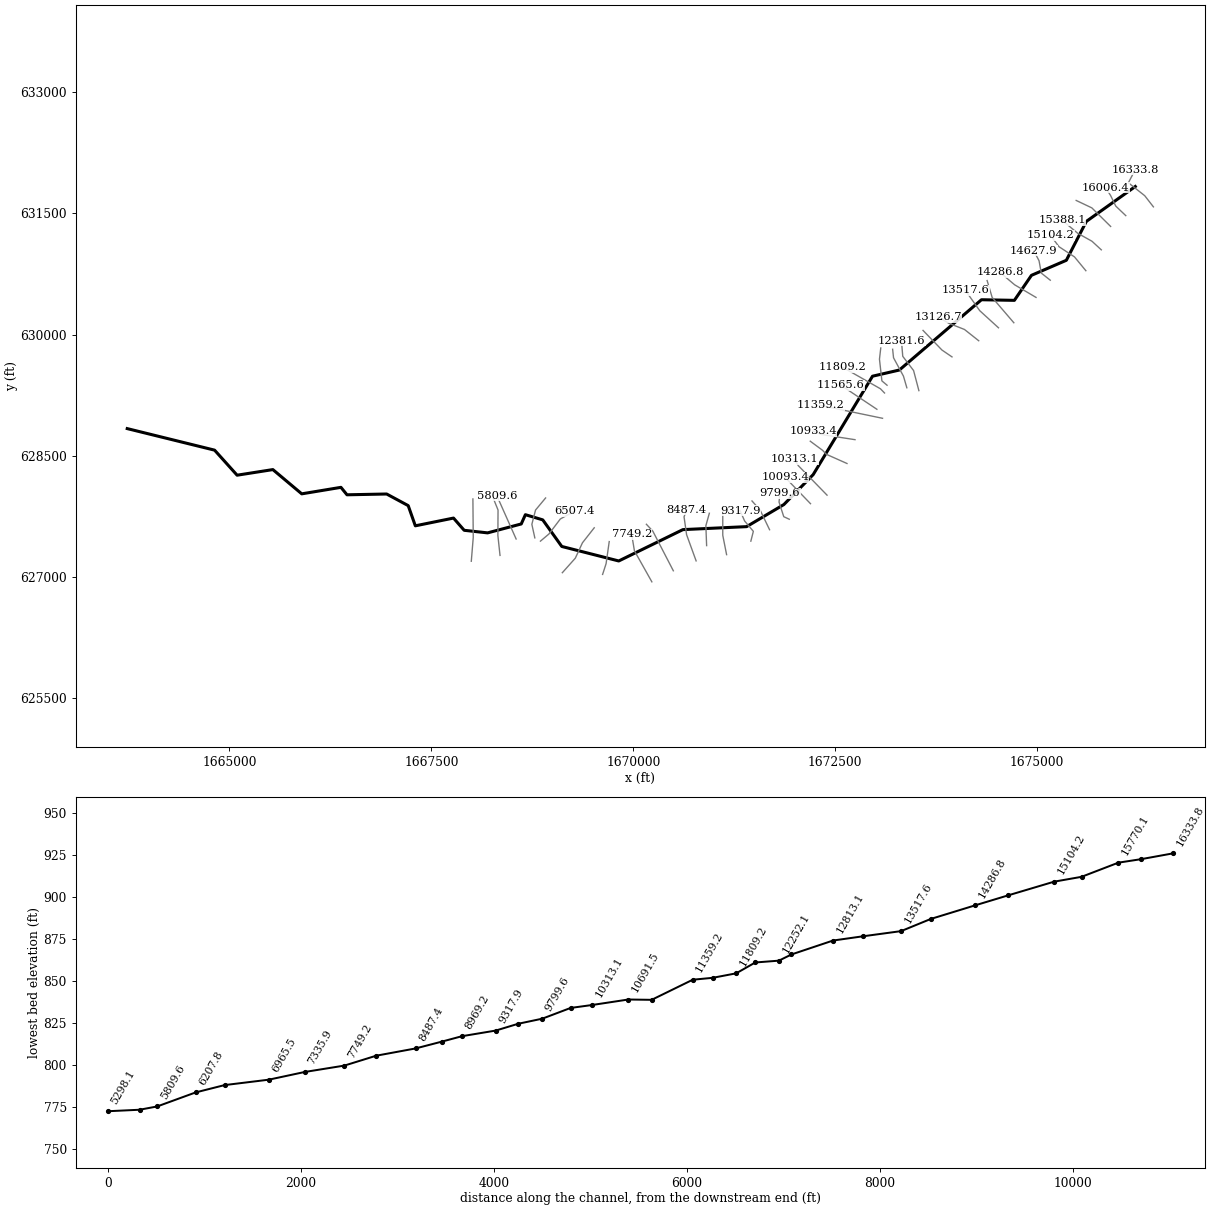
--- MNGORN.prj (project) ---

Proj Title=MNGORN
Current Plan=p01
Default Exp/Contr=0,0
English Units
Geom File=g01
Flow File=f01
Plan File=p01
BEGIN DESCRIPTION:
END DESCRIPTION:
DSS Export Rating Curves= 0
DSS Export Rating Curve Sorted= 0
DSS Export Volume Flow Curves= 0
DXF Filename=..\..\..\..\..\Engineering\Hydraulics\MNGORN\MNGORN.
DXF OffsetX= 0
DXF OffsetY= 0
DXF ScaleX= 0
DXF ScaleY= 0

--- MNGORN.p01 (plan) ---

Plan Title=Floodplain
Program Version=4.00
Geom File=g01
Flow File=f01
K Sum by GR=0
Std Step Tol=0.01
Critical Tol=0.01
Num of Std Step Trials=20
Max Error Tol=0.3
Flow Tol Ratio=0.001
Split Flow NTrial=30
Split Flow Tol=0.02
Split Flow Ratio=0.02
Log Output Level=0
Friction Slope Method=1
Unsteady Friction Slope Method=2
Unsteady Bridges Friction Slope Method=1
Global Log Level=0
CheckData=False
Run HTab=0
Run UNet=0
Run PostProcess=0
UNET Theta=0
UNET Theta Warmup=0
UNET ZTol=0
UNET ZSATol=0
UNET MxIter=0
UNET MaxInSteps=0
UNET DtIC=0
UNET DtMin=0
UNET MaxCRTS=0
UNET WFStab=0
UNET SFStab=0
UNET WFX=0
UNET SFX=0
UNET DSS MLevel=0
UNET DZMax Abort=0
UNET Convert EG Bridges=0
UNET Use Existing IB Tables=0
UNET Froude Limit=0
UNET Froude Power=0
Write IC File=0
Echo Input=False
Echo Output=False
Write Detailed=0

--- MNGORN.f01 (steady flow) ---

Flow Title=NFF Regression Equation
Program Version=4.10
Number of Profiles= 1
Profile Names=P100yr
River Rch & RM=MNGORN,Main            ,16333.8
875.6824
River Rch & RM=MNGORN,Main            ,16006.4
 922.153
River Rch & RM=MNGORN,Main            ,13825.8
1019.095
River Rch & RM=MNGORN,Main            ,12007.3
1067.154
River Rch & RM=MNGORN,Main            ,11809.2
1147.347
River Rch & RM=MNGORN,Main            ,9550.1
1189.558
River Rch & RM=MNGORN,Main            ,7335.9
1302.078
River Rch & RM=MNGORN,Main            ,4745
1441.208
River Rch & RM=MNGORN,Main            ,590.9
1534.888
Boundary for River Rch & Prof#=MNGORN,Main            , 1
Up Type= 0
Dn Type= 3
Dn Slope=0.01
DSS Import GetInterval= 0
DSS Import GetPeak= 0
DSS Import FillOption= 0

--- MNGORN.g01 (geometry) ---

Geom Title=2003 WVU SAMB 3 Meter DEM
Program Version=4.10

River Reach=MNGORN          ,Main
Reach XY= 30
     1676214.849      631831.627     1675609.121      631400.104
     1675361.421      630918.999     1674929.582      630732.964
      1674717.95      630423.415     1674310.528      630430.982
      1673293.85      629561.461     1672961.715      629485.125
     1672227.253      628268.024     1671864.385      627897.637
     1671403.022      627624.308     1670614.229      627587.451
      1669819.84       627199.67     1669114.632      627379.097
     1668879.128       627707.97     1668664.024      627772.153
     1668612.879      627657.448     1668195.952      627547.176
     1667906.274       627579.07     1667774.207      627730.216
     1667301.507      627634.428     1667213.356      627884.211
     1666946.438      628027.991     1666455.414      628018.209
     1666380.674      628110.397     1665895.183      628030.006
     1665537.746      628330.006     1665095.038      628260.561
     1664816.273      628570.435      1663734.61      628837.031

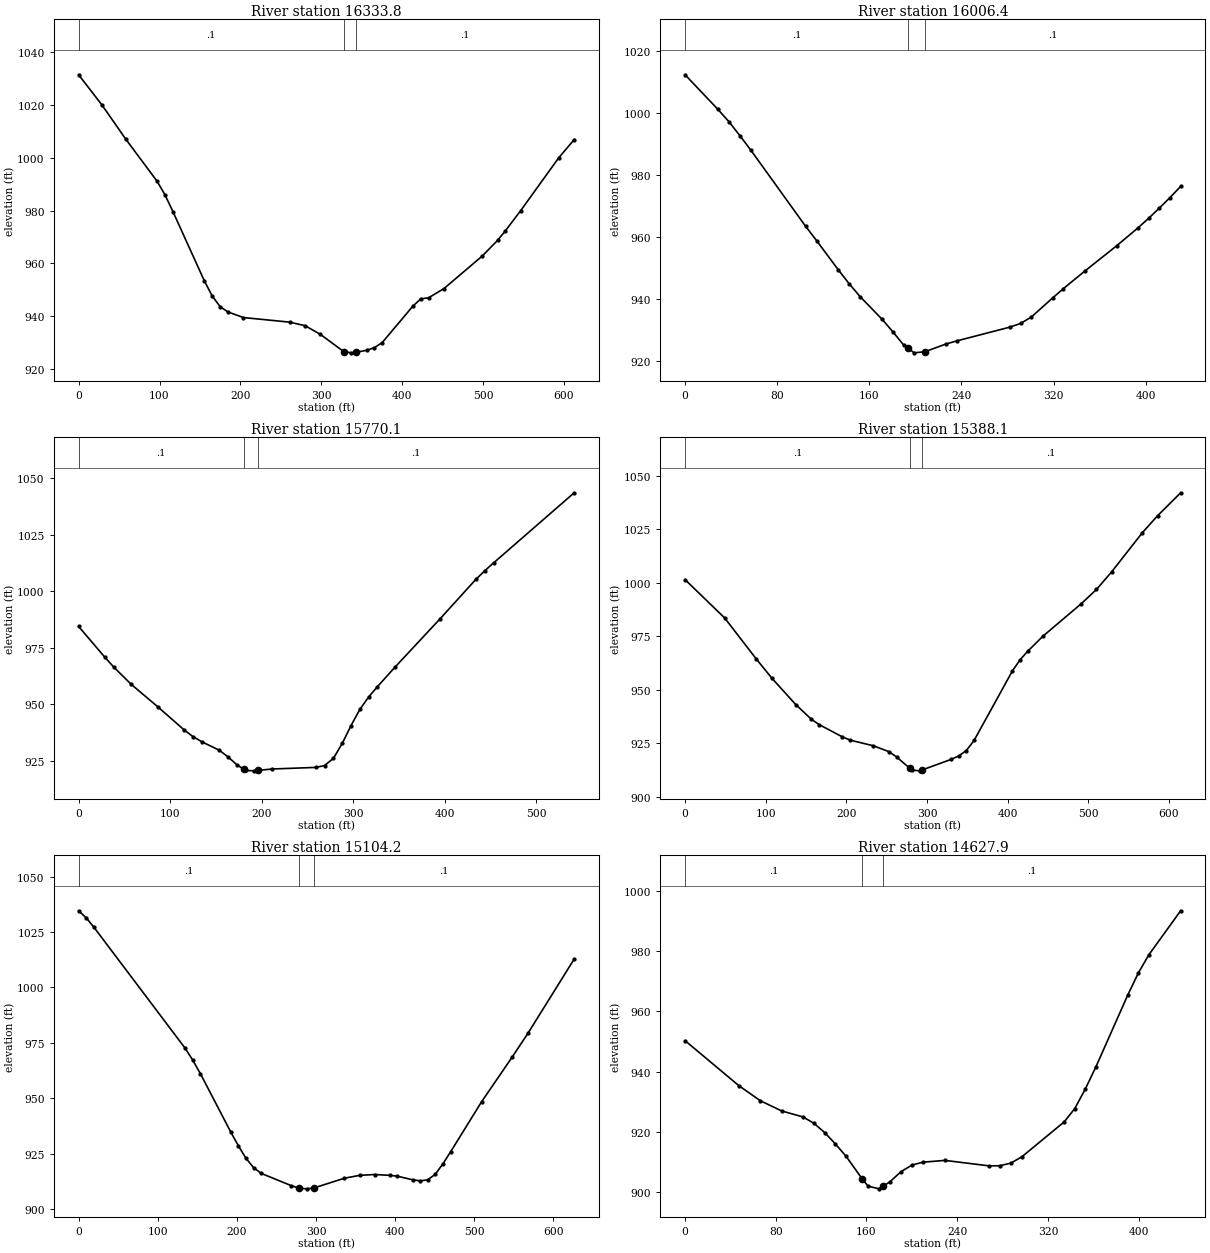
Type RM Length L Ch R = 1 ,16333.8 ,336.2,327.4,316
XS GIS Cut Line= 4
     1676439.268      631579.862      1676331.82      631717.893
     1676129.568      631877.622     1676212.705      632037.327
#Sta/Elev= 30
       0 1031.52    29.2 1019.92    58.3  1007.1    97.2  991.06   106.9   985.9
   116.6  979.63   155.5  953.33   165.2   947.6   174.9  943.63   184.5   941.6
   203.6  939.47   260.8  937.72   279.9  936.38     299  933.07   327.6  926.58
   337.2  926.08   342.7   926.3   356.3  927.05   365.8  928.05   375.4  929.99
   413.6   943.9   423.1  946.56   432.6  946.94   451.6  950.42     499  962.78
   517.9  968.71   527.4  972.24   546.4  979.94   593.7 1000.08   612.7 1006.93
#Mann= 3 , 0 , 0
       0      .1       0   327.6    .045       0   342.7      .1       0
Bank Sta=327.6,342.7
XS Rating Curve= 0 ,0
Exp/Cntr=0.3,0.1

Type RM Length L Ch R = 1 ,16006.4 ,228.6,236.3,243.8
XS GIS Cut Line= 4
     1676097.254      631471.355     1675973.267      631589.481
     1675908.092      631722.259     1675848.122      631815.973
#Sta/Elev= 30
       0  1012.2    28.5 1001.07    38.1  997.07    47.6  992.59    57.1  987.92
   104.6  963.44   114.2  958.79   133.2  949.32   142.7  944.81   152.2  940.67
   171.2  933.43   180.5   929.4   189.7  925.24   193.5  924.18     199  922.65
   208.5  923.03   226.7  925.51     236   926.5   282.2  930.94   291.4  932.12
   300.7  934.17   319.2  940.32   328.4  943.28     347  948.93   374.8  957.12
   393.3  962.88   402.6  965.98   411.9  969.26   421.2  972.67   430.4  976.25
#Mann= 3 , 0 , 0
       0      .1       0   193.5    .045       0   208.5      .1       0
Bank Sta=193.5,208.5
XS Rating Curve= 0 ,0
Exp/Cntr=0.3,0.1

Type RM Length L Ch R = 1 ,15770.1 ,374.5,381.9,386.6
XS GIS Cut Line= 3
     1675909.743      631337.669     1675677.384      631567.097
     1675483.105      631659.289
#Sta/Elev= 30
       0  984.38    28.8  970.71    38.4  966.42    57.6  958.76    86.4  948.91
   115.2   938.7   124.8  935.74   134.5  933.45   153.7  929.67   163.3  926.72
   172.9  923.27   180.7  921.21   182.5  920.73   192.1  920.56   195.7  920.74
   211.3  921.37   259.3  922.08   268.9  922.92   278.5  926.11   288.1  932.69
   297.7  940.56   307.3  947.68   316.9  953.18   326.5  957.74   346.1  966.55
     395  987.76   434.1 1005.18   443.8 1008.99   453.6 1012.52   541.6 1043.49
#Mann= 3 , 0 , 0
       0      .1       0   180.7    .045       0   195.7      .1       0
Bank Sta=180.7,195.7
XS Rating Curve= 0 ,0
Exp/Cntr=0.3,0.1

Type RM Length L Ch R = 1 ,15388.1 ,284.3,283.9,280.6
XS GIS Cut Line= 4
     1675794.194      631048.286     1675678.896      631154.463
     1675502.711      631252.609     1675306.347       631417.21
#Sta/Elev= 30
       0  1001.4      49  983.54    88.2   964.4   107.8  955.31   137.2  943.07
   156.7  936.17   166.3   933.7   195.2  927.95   204.8  926.44   233.6  923.81
   252.8  921.08   262.4  918.55   278.6  913.34   281.6  912.48   291.2  912.11
   293.6  912.47   329.6  917.41   339.2  919.01   348.8   921.6   358.4   926.3
   405.9  958.75   415.4  963.95   424.8  967.92   443.8  974.99   491.3  990.15
   510.2  996.82   529.2 1005.12   567.2 1023.38   586.2 1031.33   614.6 1041.98
#Mann= 3 , 0 , 0
       0      .1       0   278.6    .045       0   293.6      .1       0
Bank Sta=278.6,293.6
XS Rating Curve= 0 ,0
Exp/Cntr=0.3,0.1

Type RM Length L Ch R = 1 ,15104.2 ,493.5,476.3,457.1
XS GIS Cut Line= 4
     1675602.913      630790.158     1675462.224       630960.88
     1675270.495      631086.913     1675165.162      631227.422
#Sta/Elev= 30
       0 1034.59     9.6 1031.41    19.2 1027.22   134.7  972.57   144.3  967.19
   153.9  961.15   192.4  934.75     202  928.56   211.6  922.94   221.2  918.75
   230.8  916.19     269  910.62   278.6  909.55   288.1  909.22   297.7  909.65
     336  914.02   355.1   915.3   374.2  915.67   393.3  915.31   402.9  914.92
     422  913.31   431.6  912.83   441.1  913.26   450.7  915.76   460.4  920.49
   470.2  925.96   509.2  948.43   548.2  968.77   567.7  979.26   626.3 1012.81
#Mann= 3 , 0 , 0
       0      .1       0   278.6    .045       0   297.7      .1       0
Bank Sta=278.6,297.7
XS Rating Curve= 0 ,0
Exp/Cntr=0.3,0.1

Type RM Length L Ch R = 1 ,14627.9 ,321.2,341.1,360.1
XS GIS Cut Line= 4
     1675162.467      630672.635     1675051.175      630760.829
     1675023.525      630913.354     1674958.039      631037.218
#Sta/Elev= 30
       0  950.23    47.3  935.34    66.3  930.32    85.2  926.91   104.1  924.91
   113.6  922.82   123.1  919.75   132.5  915.99     142  911.86   156.3904.3116
   161.4  901.96   171.1  901.06   174.3  901.84   180.8  903.43   190.4  906.75
   200.1  908.95   209.8  909.91   229.2   910.5     268  908.69   277.6  908.73
   287.3  909.59     297  911.68   334.4  923.29   343.7   927.7     353  934.18
   362.4  941.58   390.4  965.34   399.8  972.71   409.1  978.76   437.1  993.35
#Mann= 3 , 0 , 0
       0      .1       0   156.3    .045       0   174.3      .1       0
Bank Sta=156.3,174.3
XS Rating Curve= 0 ,0
Exp/Cntr=0.3,0.1

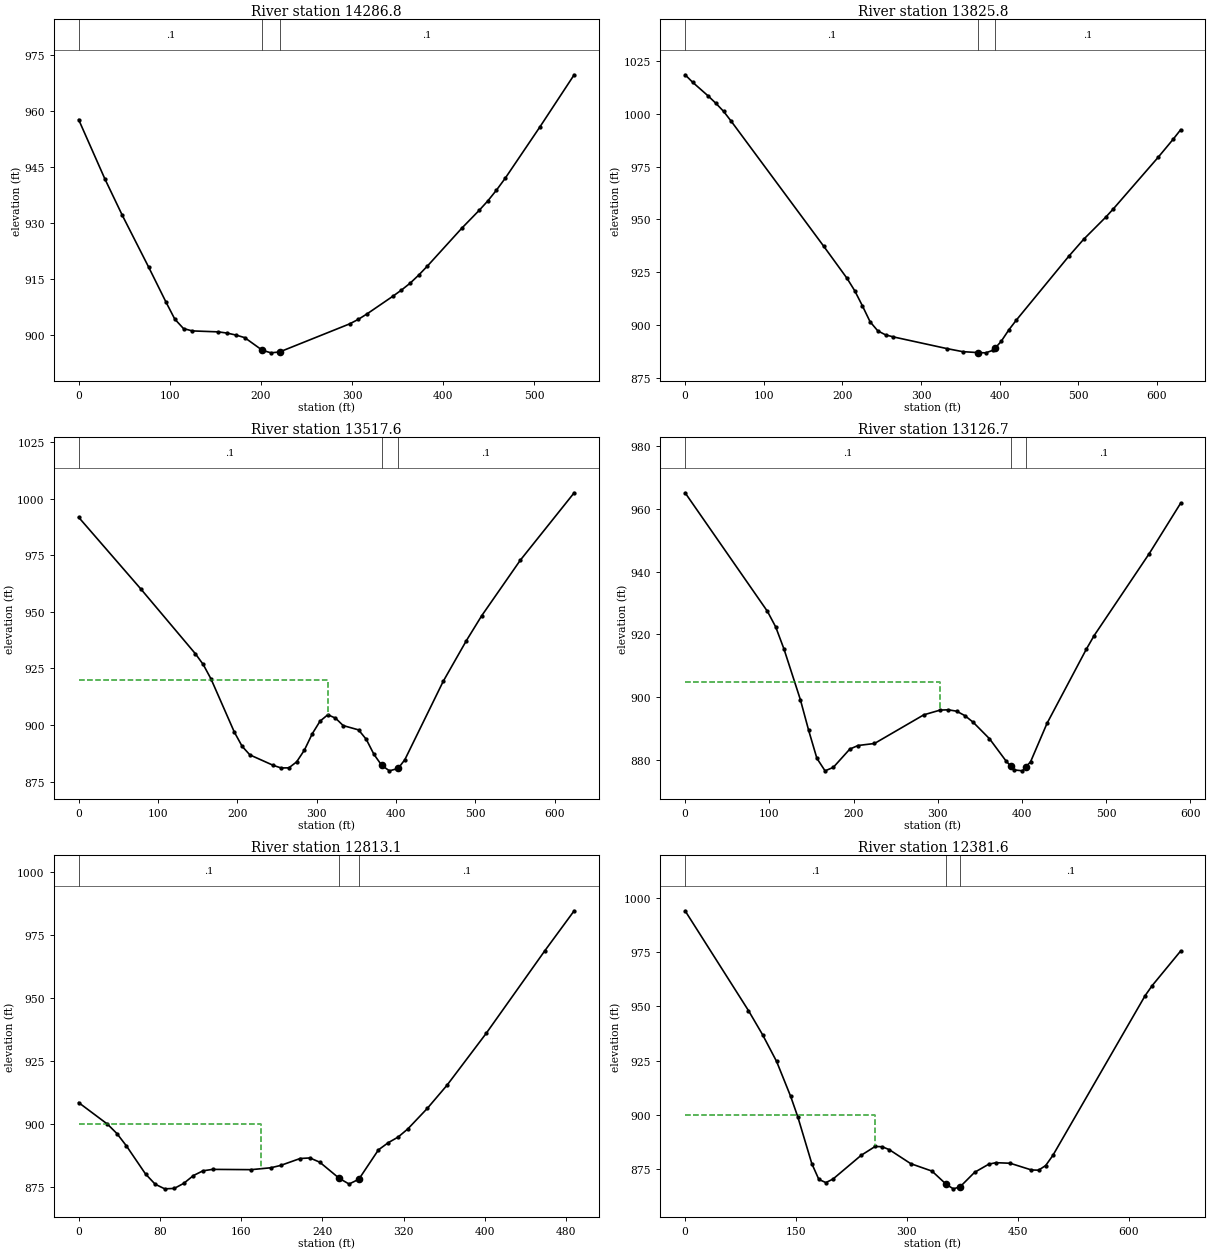
Type RM Length L Ch R = 1 ,14286.8 ,466.8,460.9,452.7
XS GIS Cut Line= 3
     1674986.034      630459.853     1674721.599      630615.519
     1674540.722      630768.447
#Sta/Elev= 30
       0  957.66    28.8  941.75      48  931.95    76.7  918.16    95.9   908.7
   105.5  904.16   115.1  901.62   124.7     901   153.4  900.74     163  900.41
   172.6  899.89   182.2   899.2   201.4  895.83     211  895.12   220.5  895.36
   297.3  902.88   306.8  904.09   316.3  905.54   344.8   910.3   354.2  911.95
   363.7  913.79   373.2  915.98   382.6  918.37   420.6  928.59   439.5  933.33
     449  935.87   458.4  938.73   467.9  941.88   505.8  955.58   543.7  969.67
#Mann= 3 , 0 , 0
       0      .1       0   201.4    .045       0   220.5      .1       0
Bank Sta=201.4,220.5
XS Rating Curve= 0 ,0
Exp/Cntr=0.3,0.1

Type RM Length L Ch R = 1 ,13825.8 ,305.8,308.2,304.1
XS GIS Cut Line= 3
     1674711.266      630146.337     1674443.231      630458.879
     1674380.565      630668.186
#Sta/Elev= 30
       0 1018.33     9.8 1014.73    29.4 1008.31    39.2 1004.84      49 1001.04
    58.8  996.31   176.5  937.23   205.9   922.2   215.7  916.33   225.5  909.18
   235.3  901.64   245.1  897.35   254.9  895.48   264.7  894.52   333.3  888.96
   352.9  887.55   373.1  887.08   382.3  886.98   392.1  888.27   394.1889.1068
   401.9  892.37   411.7  897.82   421.2  902.42   487.7  932.49   506.7  940.55
   535.2  951.16   544.7  955.02   601.7  979.39   620.7  987.88   630.2  992.37
#Mann= 3 , 0 , 0
       0      .1       0   373.1    .045       0   394.1      .1       0
Bank Sta=373.1,394.1
XS Rating Curve= 0 ,0
Exp/Cntr=0.3,0.1

Type RM Length L Ch R = 1 ,13517.6 ,376.6,391,403.3
XS GIS Cut Line= 3
     1674521.277      630083.985     1674289.182      630295.622
     1674109.552      630549.025
#Sta/Elev= 30
       0  991.88    78.5  960.12   147.2   931.5     157  926.79   166.9  920.35
   196.3  896.84   206.1  890.58   215.9  886.77   245.4  882.14   255.2     881
     265  881.04   274.8  883.68   284.6  888.88   294.5   896.1   304.3  901.67
   314.1  904.53   323.8  903.04   333.5  899.74   352.9  897.83   362.6  893.66
   372.3     887     382  882.19   391.8  879.72   402.8   880.8   411.2  884.63
   459.7  919.37   488.8   937.3   508.2  948.36   556.8  972.88   624.7  1002.7
#Mann= 3 , 0 , 0
       0      .1       0     382    .045       0   402.8      .1       0
#XS Ineff= 2 , 0
       0   314.1     920               0
Permanent Ineff=
       F       F
Bank Sta=382,402.8
XS Rating Curve= 0 ,0
Exp/Cntr=0.3,0.1

Type RM Length L Ch R = 1 ,13126.7 ,322.5,313.6,303
XS GIS Cut Line= 4
     1674276.529      629923.829     1674100.109      630063.333
     1673909.395      630138.295     1673772.362      630218.273
#Sta/Elev= 30
       0  965.03    97.8  927.34   107.6   922.4   117.4   915.4   136.9  899.29
   146.7  889.57   156.5  880.66   166.2  876.67     176  877.77   195.6  883.58
   205.4  884.72   224.9  885.36   283.5  894.47     303  895.98   312.7  896.06
   322.5  895.62   332.2  894.22     342  892.14   361.5  886.87     381  879.85
     387  878.08   390.8  876.96   400.6  876.68     405877.9891   410.3  879.56
   429.8  891.75   476.5  915.33   485.8  919.66   551.2   945.7   588.5  961.72
#Mann= 3 , 0 , 0
       0      .1       0     387    .045       0     405      .1       0
#XS Ineff= 2 , 0
       0     303     905               0
Permanent Ineff=
       F       F
Bank Sta=387,405
XS Rating Curve= 0 ,0
Exp/Cntr=0.3,0.1

Type RM Length L Ch R = 1 ,12813.1 ,432.8,431.5,427.2
XS GIS Cut Line= 3
     1673945.875      629723.928     1673821.343      629808.834
     1673587.083      630051.665
#Sta/Elev= 30
       0  908.37    28.3  899.84    37.7  896.08    47.1  891.15    65.9  880.01
    75.4  875.95    84.8  874.11    94.2  874.28   103.6   876.3     113  879.38
   122.5  881.27   131.9  881.84     170  881.73   189.3  882.48   198.9   883.4
   218.2  886.16   227.8  886.38   237.5   884.7   256.8  878.25   266.4  876.02
     276  877.93   295.3  889.59     305  892.45   314.6  894.65   324.2  897.89
   343.5  906.09   362.8  915.24   401.4  935.85   459.2  968.69   488.1  984.56
#Mann= 3 , 0 , 0
       0      .1       0   256.8    .045       0     276      .1       0
#XS Ineff= 2 , 0
       0   179.6     900               0
Permanent Ineff=
       F       F
Bank Sta=256.8,276
XS Rating Curve= 0 ,0
Exp/Cntr=0.3,0.1

Type RM Length L Ch R = 1 ,12381.6 ,132.5,129.5,125.5
XS GIS Cut Line= 4
     1673535.765      629306.719     1673470.063      629555.292
     1673336.068      629731.061     1673320.053      629922.605
#Sta/Elev= 30
       0  994.11    85.7  948.06   104.8  936.92   123.8  924.56   142.8  908.45
   152.4  899.06   171.4  877.42   180.9  870.15   190.4  868.67     200  870.29
   238.1  881.25   257.1  885.35   266.7  885.21   276.3  883.85   305.2  877.41
     334  873.97   353.2  867.88   362.8  865.79     372  866.74   391.6  873.41
   410.9  877.19   420.5  877.86   439.7   877.6   468.5   874.5   478.1   874.4
   487.7  876.53   497.4  881.18   622.3  954.96   631.9  959.62   670.3  975.54
#Mann= 3 , 0 , 0
       0      .1       0   353.2    .045       0     372      .1       0
#XS Ineff= 2 , 0
       0   257.1     900               0
Permanent Ineff=
       F       F
Bank Sta=353.2,372
XS Rating Curve= 0 ,0
Exp/Cntr=0.3,0.1

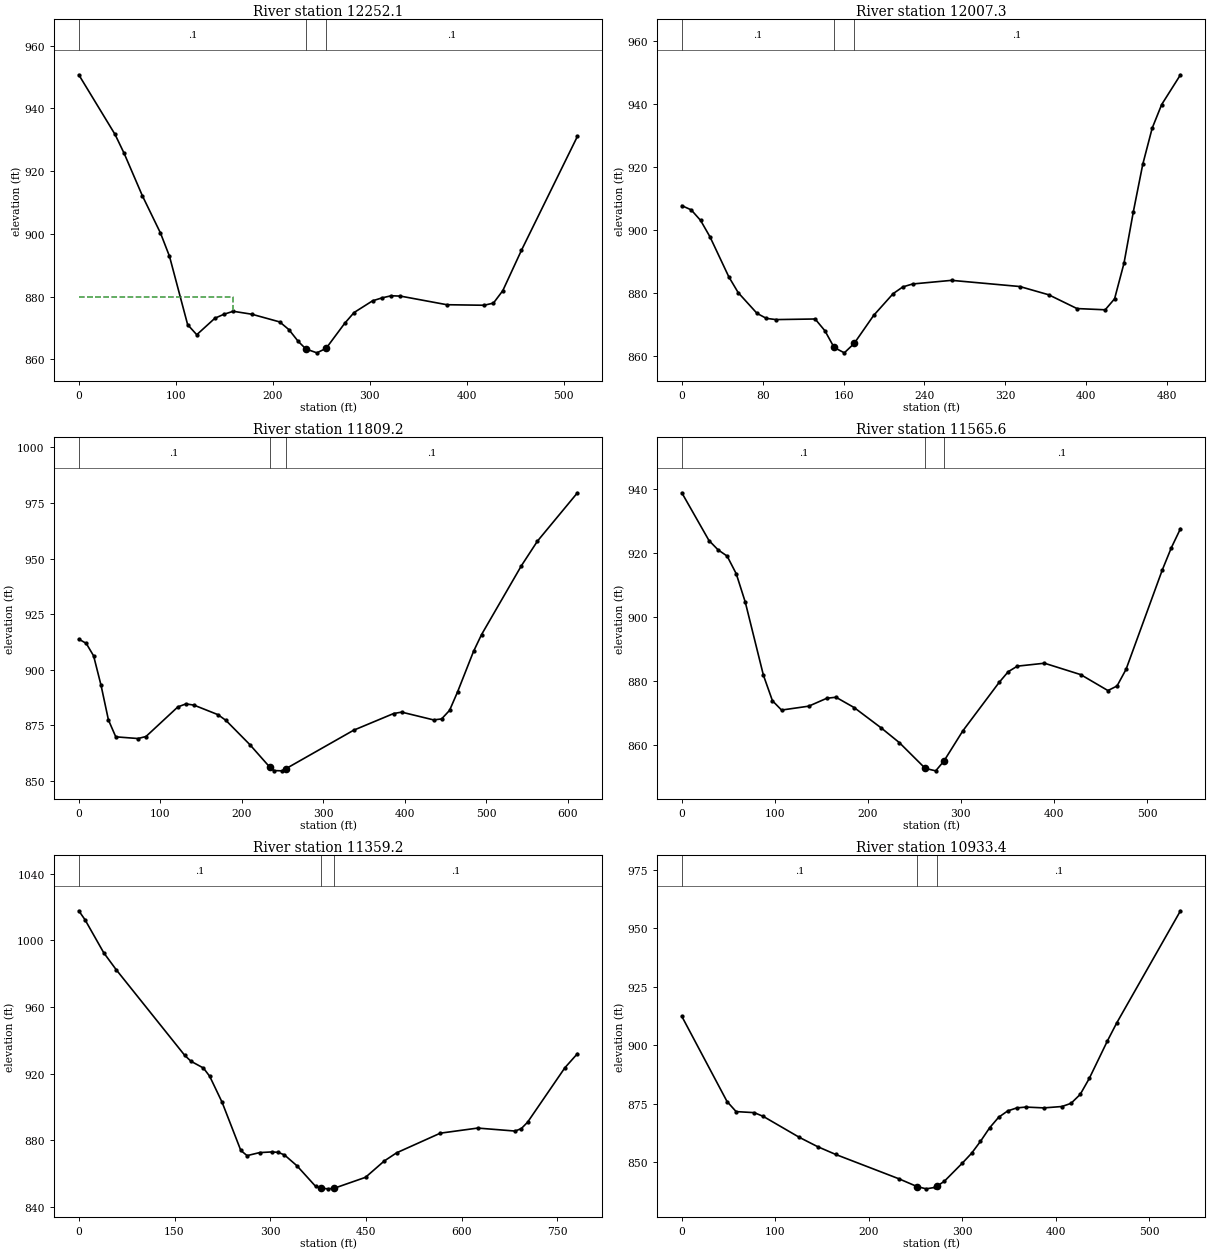
Type RM Length L Ch R = 1 ,12252.1 ,252.9,244.9,235.8
XS GIS Cut Line= 4
     1673386.677      629342.006     1673344.835      629485.661
     1673221.925      629713.067     1673210.982      629818.395
#Sta/Elev= 30
       0   950.7    37.4  931.68    46.8  925.63    65.5  912.18    84.2  900.28
    93.5  892.86   112.2  871.09   121.6  867.88   140.3  873.14   149.6   874.4
   159.2  875.35   178.4  874.41   207.1  871.96   216.6   869.5   226.2  865.75
   234.1  863.35   245.4  862.11   254.9  863.53   274.1  871.52   283.7  874.94
   302.8  878.68   312.4  879.61     322  880.29   331.5  880.19   379.4  877.44
   417.8  877.27   427.4  877.96     437   881.9   456.3   894.8     514   931.1
#Mann= 3 , 0 , 0
       0      .1       0   234.1    .045       0   254.9      .1       0
#XS Ineff= 2 , 0
       0   159.2     880               0
Permanent Ineff=
       F       F
Bank Sta=234.1,254.9
XS Rating Curve= 0 ,0
Exp/Cntr=0.3,0.1

Type RM Length L Ch R = 1 ,12007.3 ,176.1,198.1,219.1
XS GIS Cut Line= 4
     1673141.885      629373.415     1673077.816      629427.253
     1673047.793       629695.62      1673063.76      629834.352
#Sta/Elev= 30
       0  907.76     9.3  906.42    18.6  903.06    27.9  897.84    46.5  885.16
    55.8  880.13    74.4  873.56    83.7  871.96    93.3  871.58   131.9  871.77
   141.6  868.02   150.7  862.72   160.8  861.02   170.5  863.99   189.8   872.9
   209.1  879.82   218.7  881.96   228.4  882.89   266.9  884.04   334.4  882.08
     363  879.46     391  875.08   418.9  874.69   428.2  878.18   437.5  889.47
   446.8   905.9   456.1  920.92   465.4  932.37   474.8  939.88   493.4  949.32
#Mann= 3 , 0 , 0
       0      .1       0   150.7    .045       0   170.5      .1       0
Bank Sta=150.7,170.5
XS Rating Curve= 0 ,0
Exp/Cntr=0.3,0.1

Type RM Length L Ch R = 1 ,11809.2 ,243.9,243.5,241
XS GIS Cut Line= 3
     1673110.461      629277.451     1673059.802      629329.596
      1672590.93      629596.391
#Sta/Elev= 30
       0  913.76     9.1  911.88    18.2  906.24    27.3  893.03    36.4  877.41
    45.4  869.83    72.7  869.07    82.5  869.98   121.7  883.31   131.6  884.64
   141.4  884.09   170.8  879.81   180.6  877.24     210  866.33   234.4  856.23
   239.4  854.67   249.2  854.54   254.4855.5233   337.5  872.82   386.6  880.32
   396.4  880.94   435.6  877.44   445.4  877.88   455.2  881.74     465  890.02
   484.6  908.24   494.5  915.84   543.5  946.85   563.1  957.85   612.2  979.58
#Mann= 3 , 0 , 0
       0      .1       0   234.4    .045       0   254.4      .1       0
Bank Sta=234.4,254.4
XS Rating Curve= 0 ,0
Exp/Cntr=0.3,0.1

Type RM Length L Ch R = 1 ,11565.6 ,197.3,206.4,214.6
XS GIS Cut Line= 2
     1673015.908      629075.928     1672569.946      629373.246
#Sta/Elev= 30
       0  938.81    29.2  923.88      39  920.96    48.7  919.02    58.5  913.49
    68.2  904.63    87.7  881.77    97.4  873.79   107.2  870.87   136.4  872.09
   155.9  874.57   165.7  874.88   185.2  871.66   214.4  865.27   233.9  860.67
   261.7  852.63   272.9  851.87   281.7854.9088   302.1  864.39   341.1  879.53
   350.8  882.85   360.6   884.6   389.8  885.52   428.8  881.95     458  876.97
   467.8   878.4   477.5  883.61   516.5  914.72   526.2  921.65     536   927.6
#Mann= 3 , 0 , 0
       0      .1       0   261.7    .045       0   281.7      .1       0
Bank Sta=261.7,281.7
XS Rating Curve= 0 ,0
Exp/Cntr=0.3,0.1

Type RM Length L Ch R = 1 ,11359.2 ,422.9,425.8,426
XS GIS Cut Line= 2
     1673085.807      628964.556     1672320.738       629123.25
#Sta/Elev= 30
       0 1017.81     9.8  1012.4    39.1  992.58    58.6  982.41     166  930.94
   175.8  927.39   195.3  923.32   205.1  918.39   224.6  902.71   253.9   873.8
   263.7  870.68   283.2   872.5   302.8  872.92   312.5  872.65   322.3   871.1
   341.8  864.61   371.1  852.22     379851.1156   390.7  850.73   400.4  851.11
   449.3  857.65   478.6  867.45   498.1  872.39   566.5  884.18   625.1  887.24
   683.7  885.45   693.4  886.94   703.2  890.74   761.8  923.54   781.4  931.96
#Mann= 3 , 0 , 0
       0      .1       0     379    .045       0   400.4      .1       0
Bank Sta=379,400.4
XS Rating Curve= 0 ,0
Exp/Cntr=0.3,0.1

Type RM Length L Ch R = 1 ,10933.4 ,256.3,241.9,226.7
XS GIS Cut Line= 3
     1672744.962       628700.02     1672333.343      628763.652
     1672223.981      628805.403
#Sta/Elev= 30
       0  912.41    48.4  876.03    58.1  871.73    77.5  871.28    87.2  869.67
   125.9   860.7   145.3  856.76   164.7  853.42   232.5     843   251.8   839.7
   261.5  838.74   271.2  839.38   272.7  839.78   280.9  841.97   300.3  849.78
     310   853.9   319.6  859.03   329.3  864.77     339   869.3   348.7  872.01
   358.4   873.3   368.1  873.66   387.4  873.31   406.8   873.9   416.5  875.26
   426.3  879.07     436  885.89   455.5  901.98   465.3  909.54   533.6  957.49
#Mann= 3 , 0 , 0
       0      .1       0   251.8    .045       0   272.7      .1       0
Bank Sta=251.8,272.7
XS Rating Curve= 0 ,0
Exp/Cntr=0.3,0.1

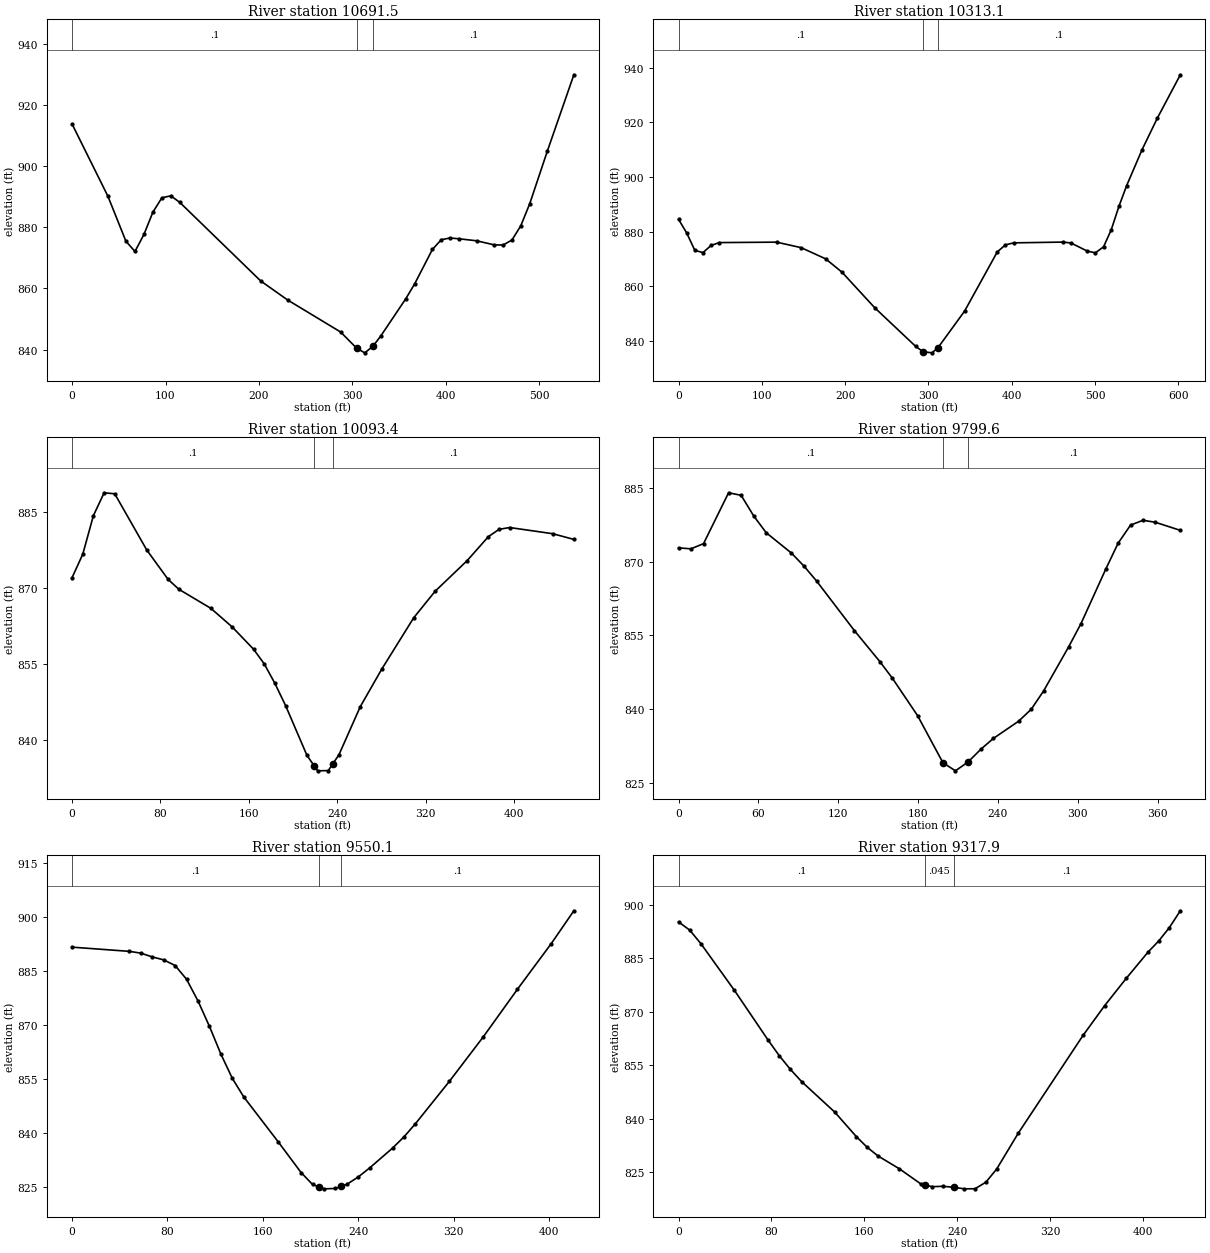
Type RM Length L Ch R = 1 ,10691.5 ,376.5,378.4,377.9
XS GIS Cut Line= 4
     1672645.666      628405.446     1672391.072      628518.675
     1672343.185      628568.492     1672191.022      628681.054
#Sta/Elev= 30
       0  913.73    38.4   890.1    57.6  875.43    67.3  872.07    76.9  877.62
    86.5  884.92    96.1  889.61   105.7  890.26   115.3  888.11   201.8  862.45
   230.6  856.22   287.3  845.76   304.6  840.44   313.2  838.93   321.8  841.01
   330.5  844.49   357.2  856.64   366.7  861.52   385.6  872.72   395.1  875.92
   404.5  876.47     414  876.22   432.9  875.56   451.8  874.23   461.3  874.17
   470.8  875.83   480.2  880.46   489.7  887.61   508.6  904.86     537  929.83
#Mann= 3 , 0 , 0
       0      .1       0   304.6    .045       0   321.8      .1       0
Bank Sta=304.6,321.8
XS Rating Curve= 0 ,0
Exp/Cntr=0.3,0.1

Type RM Length L Ch R = 1 ,10313.1 ,219.6,219.7,219.4
XS GIS Cut Line= 3
     1672398.819      628013.747     1672042.627      628379.107
     1671996.413      628458.777
#Sta/Elev= 30
       0  884.51     9.8  879.51    19.6  873.12    29.4  872.34    39.2  874.98
    49.1  875.99   117.8  876.15   147.2  874.13   176.6  870.04   196.2  865.16
   235.5  852.14   284.6  838.02   293.4  836.06   304.2  835.63   311.4837.4814
   343.4   850.9   382.7   872.6   392.5  875.16   402.3  875.89   461.2  876.17
     471  875.86   490.6  872.89   500.4  872.24   510.2  874.42   519.5  880.71
   528.7  889.25   537.9  896.81   556.3  909.89   574.7  921.49   602.4  937.42
#Mann= 3 , 0 , 0
       0      .1       0   293.4    .045       0   311.4      .1       0
Bank Sta=293.4,311.4
XS Rating Curve= 0 ,0
Exp/Cntr=0.3,0.1

Type RM Length L Ch R = 1 ,10093.4 ,303.8,293.8,283.2
XS GIS Cut Line= 2
     1672193.932      627908.167     1671878.584      628234.749
#Sta/Elev= 30
       0  872.02     9.7  876.66    19.3  884.26      29  888.77    38.6  888.57
    67.6  877.47    86.9  871.68    96.6  869.73   125.6  865.96   144.9  862.29
   164.2   857.9   173.9     855   183.5  851.16   193.2  846.77   212.5  836.96
     219834.9064   222.2   833.9   231.8  833.95     236835.3083   241.5  837.09
   260.8  846.58   280.1  853.94   309.1   864.1   328.4  869.32   357.4  875.37
   376.7  880.12   386.4  881.56     396  881.91   434.7   880.7     454  879.57
#Mann= 3 , 0 , 0
       0      .1       0     219    .045       0     236      .1       0
Bank Sta=219,236
XS Rating Curve= 0 ,0
Exp/Cntr=0.3,0.1

Type RM Length L Ch R = 1 ,9799.6  ,245.4,249.5,251.7
XS GIS Cut Line= 4
     1671931.129       627715.69     1671862.835      627747.372
     1671804.522      627927.852     1671815.427      628039.342
#Sta/Elev= 30
       0  872.81     9.4  872.62    18.8  873.68    37.6  884.01      47   883.5
    56.5  879.29    65.9  875.88    84.8  871.76    94.2  869.12   103.7  866.08
   132.2  855.97   151.2  849.71   160.6  846.34   179.6  838.71   198.6  829.16
     208  827.49   217.5  829.28     227  831.85   236.5  834.07   255.5  837.58
     265  840.01   274.3  843.74     293  852.65   302.3  857.38     321   868.5
   330.3  873.78   339.6  877.44     349  878.42   358.3  878.01     377  876.37
#Mann= 3 , 0 , 0
       0      .1       0   198.6    .045       0   217.5      .1       0
Bank Sta=198.6,217.5
XS Rating Curve= 0 ,0
Exp/Cntr=0.3,0.1

Type RM Length L Ch R = 1 ,9550.1  ,225.6,232.2,237
XS GIS Cut Line= 3
     1671687.224      627586.147     1671570.514      627828.284
     1671469.726      627941.986
#Sta/Elev= 30
       0  891.71      48  890.54    57.6  890.05    67.2     889    76.8  888.17
    86.4   886.6      96  882.77   105.6  876.72   115.2  869.65   124.8  861.93
   134.4  855.17     144  850.01   172.8  837.55     192     829   201.6  825.68
   206.7  825.03   211.2  824.46   220.8  824.56   225.7825.1481   230.4  825.71
     240  827.78   249.6  830.31   268.8  835.83   278.3  838.93   287.8  842.55
   316.3  854.35   344.8  866.77   373.3  879.95   401.8  892.72   420.7  901.83
#Mann= 3 , 0 , 0
       0      .1       0   206.7    .045       0   225.7      .1       0
Bank Sta=206.7,225.7
XS Rating Curve= 0 ,0
Exp/Cntr=0.3,0.1

Type RM Length L Ch R = 1 ,9317.9  ,363.5,348.6,331.3
XS GIS Cut Line= 4
     1671455.399      627444.809     1671486.429      627566.152
     1671378.357      627694.258     1671322.065      627821.892
#Sta/Elev= 30
       0  895.26     9.6  892.96    19.3  889.15    48.2  876.04    77.1  862.16
    86.7  857.79    96.3  853.94     106   850.5   134.6  841.93   153.2  835.06
   162.5  832.08   171.8  829.65   190.4  826.01     209  821.74   212.5821.4731
   218.4  821.02   227.7  821.12     237  820.86   246.3  820.41   255.6  820.44
   264.9  822.29   274.2  825.99   292.8  836.04   348.6  863.45   367.2  871.78
   385.8  879.43   404.4  886.73   413.8  889.92     423  893.69   432.4  898.38
#Mann= 3 , 0 , 0
       0      .1       0   212.5    .045       0     237      .1       0
Bank Sta=212.5,237
XS Rating Curve= 0 ,0
Exp/Cntr=0.3,0.1

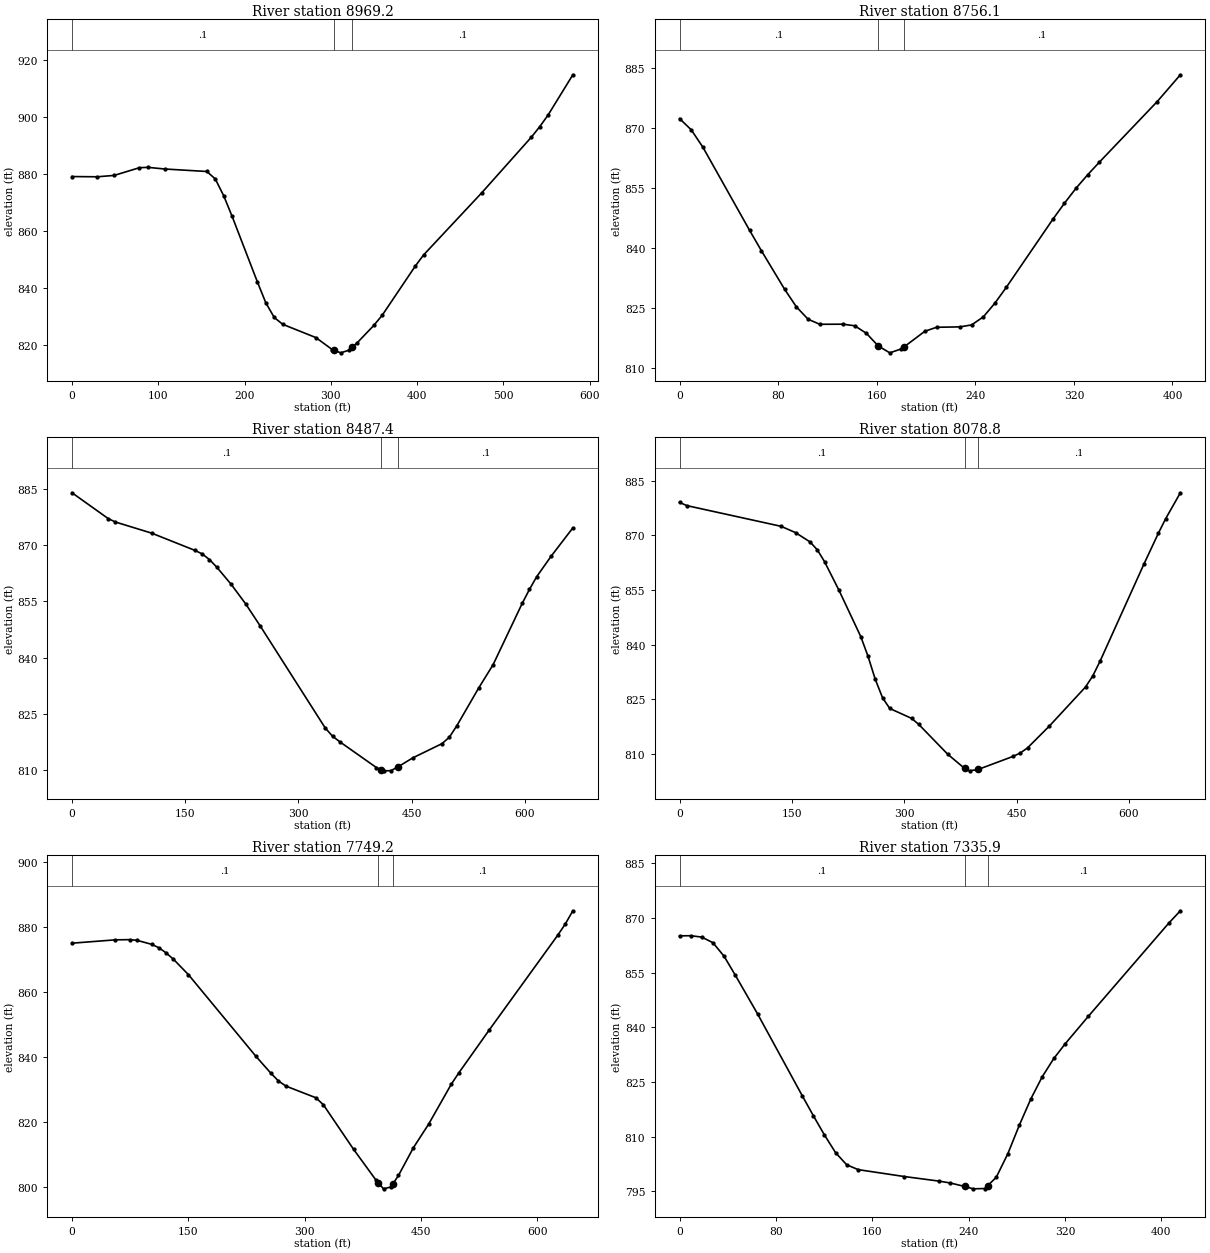
Type RM Length L Ch R = 1 ,8969.2  ,212.3,213.1,213.7
XS GIS Cut Line= 3
     1671155.128      627277.816     1671107.704      627517.318
     1671107.676      627853.697
#Sta/Elev= 30
       0  879.04    29.3  878.96    48.8  879.44    78.1  882.15    87.9  882.28
   107.4   881.7   156.3  880.82     166  878.22   175.8   872.3   185.6  865.02
   214.8  842.04   224.6  834.67   234.4   829.5   244.2   827.1   282.6  822.44
   301.8  818.18     304817.9272   311.4  817.07     321     818     325819.0939
   330.6  820.62   349.9  826.75   359.5  830.27   397.9  847.58   407.5  851.49
   474.8   873.3   532.5  892.92   542.1  896.58   551.7  900.63   580.5  914.82
#Mann= 3 , 0 , 0
       0      .1       0     304    .045       0     325      .1       0
Bank Sta=304,325
XS Rating Curve= 0 ,0
Exp/Cntr=0.3,0.1

Type RM Length L Ch R = 1 ,8756.1  ,266,268.7,270.7
XS GIS Cut Line= 3
     1670907.802      627389.512     1670898.537      627635.801
     1670941.423      627789.861
#Sta/Elev= 30
       0  872.33     9.5  869.52      19  865.15    56.9  844.36    66.4  839.31
    85.3  829.64    94.8  825.27   104.3  822.17   113.8  820.91   132.7  820.93
   142.2  820.53   151.7  818.63   161.2   815.5   170.6  813.77   180.1  814.77
     182815.2161   199.1  819.17   208.6  820.16   227.5  820.26     237  820.75
   246.5  822.76   255.9  826.19   265.3  830.21   302.9  847.15   312.3  851.15
   321.7  854.91   331.1  858.26   340.5  861.38   387.6  876.58   406.4  883.28
#Mann= 3 , 0 , 0
       0      .1       0   161.2    .045       0     182      .1       0
Bank Sta=161.2,182
XS Rating Curve= 0 ,0
Exp/Cntr=0.3,0.1

Type RM Length L Ch R = 1 ,8487.4  ,399.7,408.6,415.3
XS GIS Cut Line= 4
     1670777.842      627200.623     1670659.763      627525.086
     1670628.466      627745.379      1670661.74      627835.388
#Sta/Elev= 30
       0  884.04      48  877.14    57.6  876.22   105.5  873.26     163  868.64
   172.6   867.7   182.2  866.19   191.8  864.18     211  859.56   230.2  854.34
   249.4  848.47   335.7  821.17   345.3     819     355   817.5   403.3  810.64
   409.9  810.03     413  809.75   422.7   809.8   432.4  810.86   451.7  813.22
   490.4  817.02   500.1  818.74   509.7  821.68   538.8  831.82   558.1  838.11
   596.6  854.46   606.2   858.2   615.8   861.6     635  867.09   663.8  874.66
#Mann= 3 , 0 , 0
       0      .1       0   409.9    .045       0   432.4      .1       0
Bank Sta=409.9,432.4
XS Rating Curve= 0 ,0
Exp/Cntr=0.3,0.1

Type RM Length L Ch R = 1 ,8078.8  ,328.2,329.6,329.3
XS GIS Cut Line= 3
     1670495.654       627078.28     1670241.969      627568.074
     1670162.203      627653.545
#Sta/Elev= 30
       0  879.08     9.7  878.19   135.5  872.51   154.8  870.78   174.2  868.22
   183.9  866.06   193.5  862.82   212.9  854.92   241.9  842.25   251.6  836.83
   261.3  830.49     271  825.45   280.6  822.52   309.7  819.81   319.3  818.15
     358  809.96   380.5  806.07   387.1  805.41   398.5805.7839   445.1  809.37
   454.8   810.3   464.5  811.71   493.5  817.67   541.9  828.42   551.6  831.46
   561.3   835.5   619.8  862.12   639.3  870.68     649  874.65   668.5  881.71
#Mann= 3 , 0 , 0
       0      .1       0   380.5    .045       0   398.5      .1       0
Bank Sta=380.5,398.5
XS Rating Curve= 0 ,0
Exp/Cntr=0.3,0.1

Type RM Length L Ch R = 1 ,7749.2  ,427.8,413.3,397.4
XS GIS Cut Line= 4
     1670229.731      626941.588     1670170.384      627047.145
     1670013.984      627325.326     1669980.201      627528.003
#Sta/Elev= 30
       0  875.01    55.9  876.04    74.5   876.1    83.8  875.89   102.5  874.67
   111.8  873.64   121.1  872.07   130.8  870.07   150.1  865.34   237.1  840.24
   256.5  835.02   266.2  832.66   275.8  831.09   314.5   827.5   324.2  825.31
   362.9   811.7   391.9   802.2   394.9801.3729   401.6  799.52   411.2   800.1
   413.9  801.09   420.9  803.64   440.2  812.19   459.8  819.41   489.2  831.77
   498.9  835.23   538.1  848.41   626.1  877.42   635.9  880.88   645.7  884.97
#Mann= 3 , 0 , 0
       0      .1       0   394.9    .045       0   413.9      .1       0
Bank Sta=394.9,413.9
XS Rating Curve= 0 ,0
Exp/Cntr=0.3,0.1

Type RM Length L Ch R = 1 ,7335.9  ,376.5,370.4,363
XS GIS Cut Line= 3
     1669619.957      627033.211     1669662.949      627165.214
      1669702.03      627439.517
#Sta/Elev= 30
       0  865.12     9.3  865.17    18.5  864.78    27.8  863.23      37  859.52
    46.3  854.33    64.8   843.7   101.8   821.3   111.1  815.77   120.3  810.48
   129.6   805.6   138.8  802.28   148.4  800.95   186.6  799.06   215.3  797.81
   224.8  797.29   236.8796.3287   243.9  795.68   253.5  795.77   255.8  796.52
     263  798.85   272.6   805.3   282.1   813.1   291.7  820.35   301.2  826.46
   310.8  831.46   320.4  835.56   339.5  843.05   406.4  868.67   415.9  872.01
#Mann= 3 , 0 , 0
       0      .1       0   236.8    .045       0   255.8      .1       0
Bank Sta=236.8,255.8
XS Rating Curve= 0 ,0
Exp/Cntr=0.3,0.1

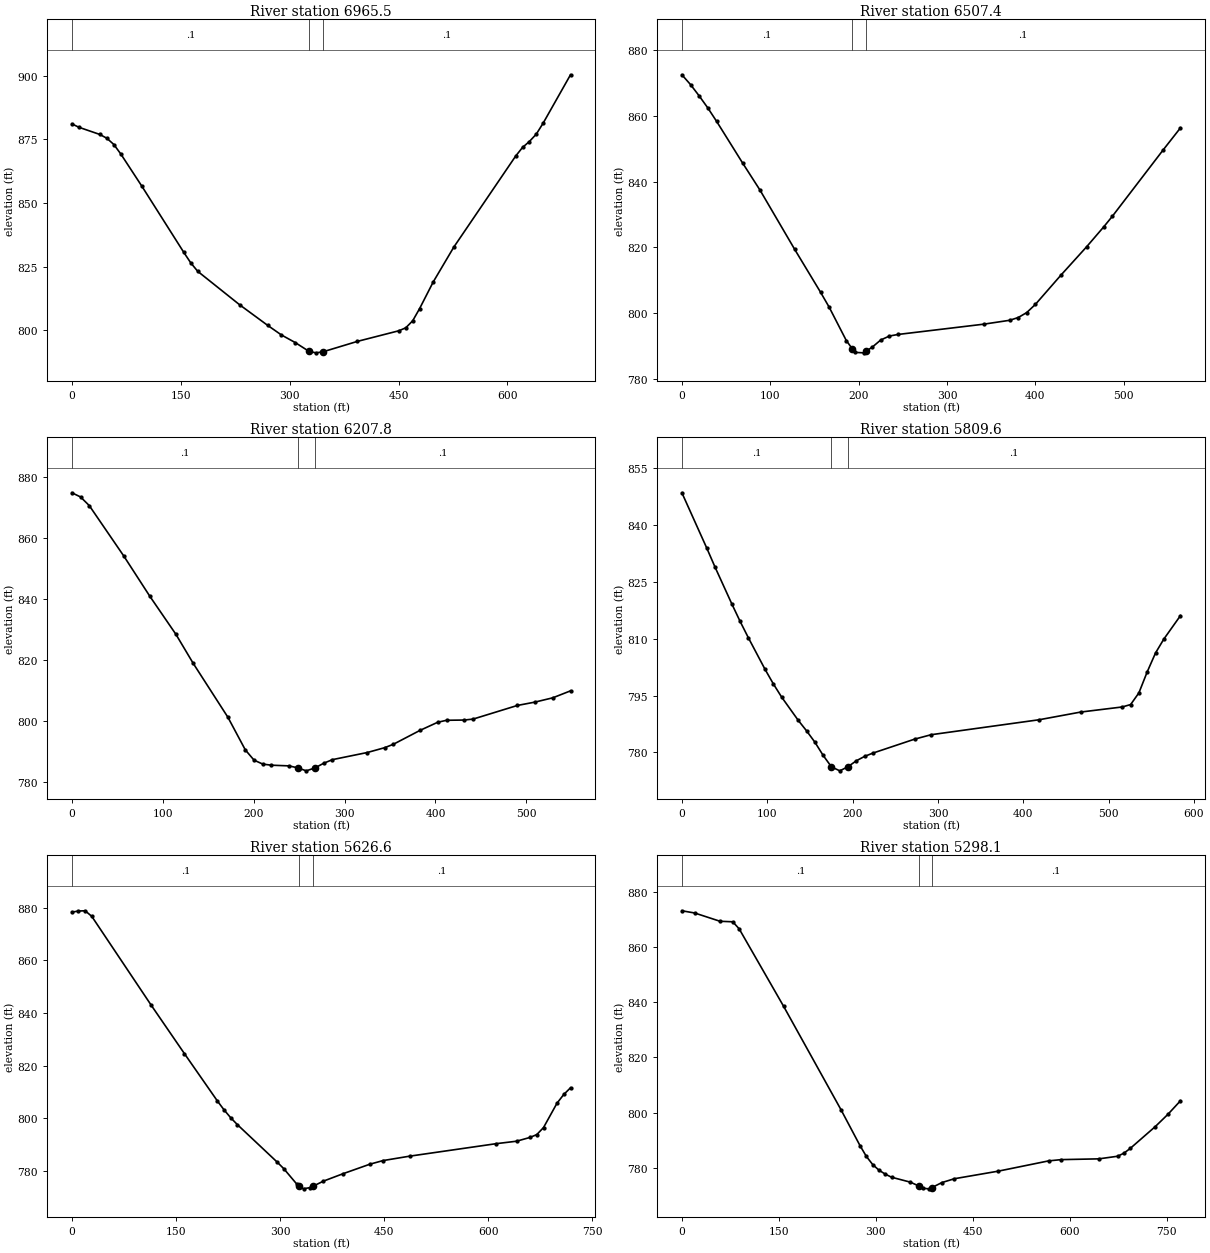
Type RM Length L Ch R = 1 ,6965.5  ,462.4,458.1,452.5
XS GIS Cut Line= 4
     1669121.477      627054.478     1669282.075      627234.015
     1669370.379      627424.214     1669516.442      627610.034
#Sta/Elev= 30
       0   881.1     9.6  879.77    38.5  876.94    48.2  875.44    57.8  872.99
    67.4  869.25    96.4  856.59   154.2  830.57   163.8  826.45   173.4  823.13
   231.2  809.97   269.5  801.95   288.5  798.16   307.6  795.16   326.7  791.68
   336.2  791.11   345.7   791.5   393.4  795.62   450.6   799.8     460  800.96
   469.5  803.72   478.9  808.44   497.8  818.99   526.2   832.7   611.3  868.43
   620.8  871.84   630.2  874.16   639.7  877.05   649.1  881.33   686.9   900.4
#Mann= 3 , 0 , 0
       0      .1       0   326.7    .045       0   345.7      .1       0
Bank Sta=326.7,345.7
XS Rating Curve= 0 ,0
Exp/Cntr=0.3,0.1

Type RM Length L Ch R = 1 ,6507.4  ,289.2,299.6,306.5
XS GIS Cut Line= 4
     1668850.511      627444.941     1668955.666       627533.47
     1669096.994      627719.389     1669266.309      627812.563
#Sta/Elev= 30
       0  872.51     9.8  869.52    19.6  866.07    29.5  862.36    39.3  858.33
    68.7  845.66    88.4  837.41   127.6   819.4   156.9  806.34   166.6  801.82
   186.1  791.61     193  789.06   195.8  788.02   205.6  787.88     208   788.3
   215.3  789.58     225  791.78   234.8  792.99   244.5  793.47   341.8  796.61
     371  797.79   380.7  798.63   390.3  800.14     400   802.6     429  811.53
     458  820.14   477.3  826.18     487  829.38   544.9  849.71   564.3  856.36
#Mann= 3 , 0 , 0
       0      .1       0     193    .045       0     208      .1       0
Bank Sta=193,208
XS Rating Curve= 0 ,0
Exp/Cntr=0.3,0.1

Type RM Length L Ch R = 1 ,6207.8  ,369.8,398.2,413.3
XS GIS Cut Line= 4
     1668780.909      627485.291     1668744.169      627652.926
      1668789.59      627829.258     1668914.373      627978.998
#Sta/Elev= 30
       0   874.7     9.5  873.33    19.1   870.5    57.2  853.91    85.8  840.73
   114.4   828.3   133.5  818.74   171.6   801.1   190.8  790.38   200.4  787.02
     210  785.72   219.5  785.36   238.7  785.14   248.3  784.51   257.9  783.51
   267.4  784.47     277  785.99   286.6  787.18     325  789.52   344.1   791.1
   353.7  792.22   382.9  796.76   402.4  799.43   412.2  800.09   431.7  800.17
   441.4  800.48   490.1  804.95   509.6  806.06   529.1  807.46   548.6  809.74
#Mann= 3 , 0 , 0
       0      .1       0   248.3    .045       0   267.4      .1       0
Bank Sta=248.3,267.4
XS Rating Curve= 0 ,0
Exp/Cntr=0.3,0.1

Type RM Length L Ch R = 1 ,5809.6  ,191.7,183,171.8
XS GIS Cut Line= 2
     1668549.465      627471.523      1668311.79      628005.059
#Sta/Elev= 30
       0   848.5    29.2  833.88    38.9  828.86    58.4  819.23    68.1  814.62
    77.9  810.24    97.4  801.93   107.1   798.1   116.8  794.62   136.3  788.47
     146  785.72   155.8  782.71   165.5  779.22   175.2   776.2     185  775.15
   194.7  776.26   204.4  777.81   214.2  778.98   223.9  779.84   272.6  783.51
     292  784.68   418.6  788.63   467.3  790.66   515.9     792   525.7  792.64
   535.4  795.72   545.1  801.25   554.9  806.26   564.6  809.91   584.1   816.1
#Mann= 3 , 0 , 0
       0      .1       0   175.2    .045       0   194.7      .1       0
Bank Sta=175.2,194.7
XS Rating Curve= 0 ,0
Exp/Cntr=0.3,0.1

Type RM Length L Ch R = 1 ,5626.6  ,327.3,328.5,327.6
XS GIS Cut Line= 4
     1668349.985      627268.351     1668323.447       627514.91
     1668325.483      627830.031     1668266.939      627974.294
#Sta/Elev= 30
       0  878.34     9.5  878.77    19.1  878.86    28.6  876.75   114.4  842.94
   162.1  824.61   209.8  806.55   219.4  803.17   228.9  800.21   238.4  797.62
   295.7   783.4   305.3  780.88   324.4  774.92     328774.2642   333.9  773.18
   343.5  773.68     347774.0926   362.6  776.11   391.2  778.96   429.4  782.53
   448.5  783.92   486.7  785.59   611.8  790.35     641  791.28   660.4  792.72
   670.2   793.8   679.9  796.47   699.3  805.71   709.1  809.05   718.8  811.58
#Mann= 3 , 0 , 0
       0      .1       0     328    .045       0     347      .1       0
Bank Sta=328,347
XS Rating Curve= 0 ,0
Exp/Cntr=0.3,0.1

Type RM Length L Ch R = 1 ,5298.1  ,552.6,553,550.6
XS GIS Cut Line= 3
     1667994.408      627196.272     1668018.602       627490.55
      1668014.25      627966.788
#Sta/Elev= 30
       0  873.27    19.7  872.47      59  869.46    78.7  869.27    88.6  866.72
   157.5  838.54   246.1  801.06   275.6  787.99   285.4  784.08   295.3  781.09
     305  779.06   314.7  777.63   324.4  776.51   353.6  774.71   366.8773.3047
     373  772.48   382.8  772.29   386.8  772.74   402.2  774.56   421.6  775.96
   489.7  778.72   567.4  782.44   586.9   782.9   645.2  783.18   674.3  784.13
     684  785.25   693.8  786.98   732.6  794.92   752.1  799.36   771.5  804.28
#Mann= 3 , 0 , 0
       0      .1       0   366.8    .045       0   386.8      .1       0
Bank Sta=366.8,386.8
XS Rating Curve= 0 ,0
Exp/Cntr=0.3,0.1