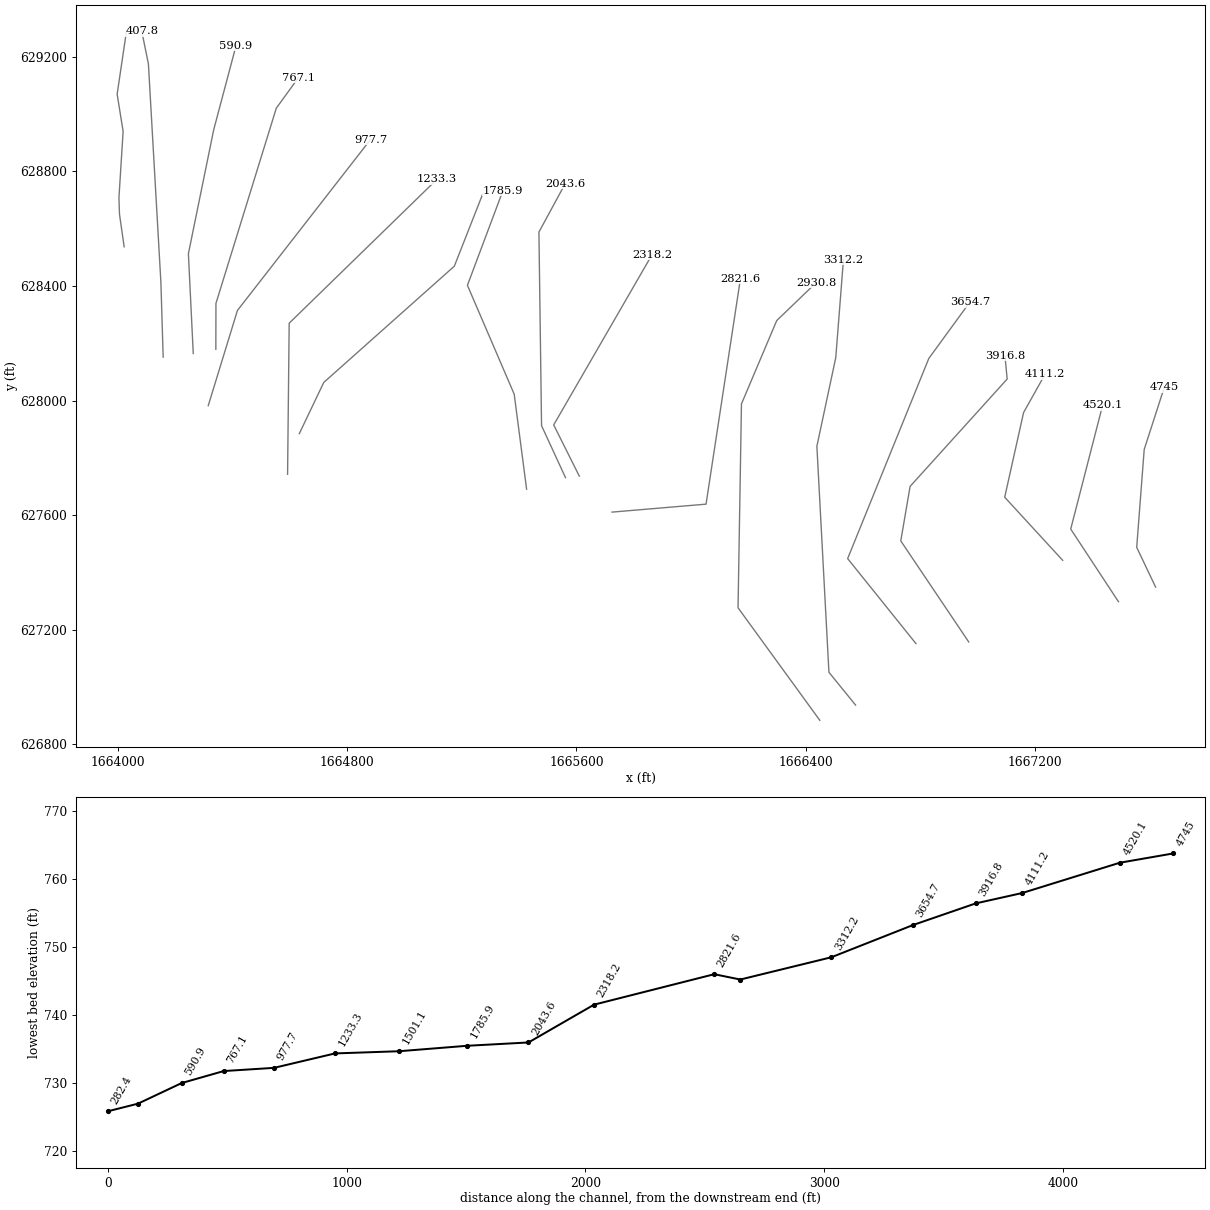
HEC-RAS study MNGORN.prj: MNGORN

--- MNGORN.g01 (geometry) --- (continued)

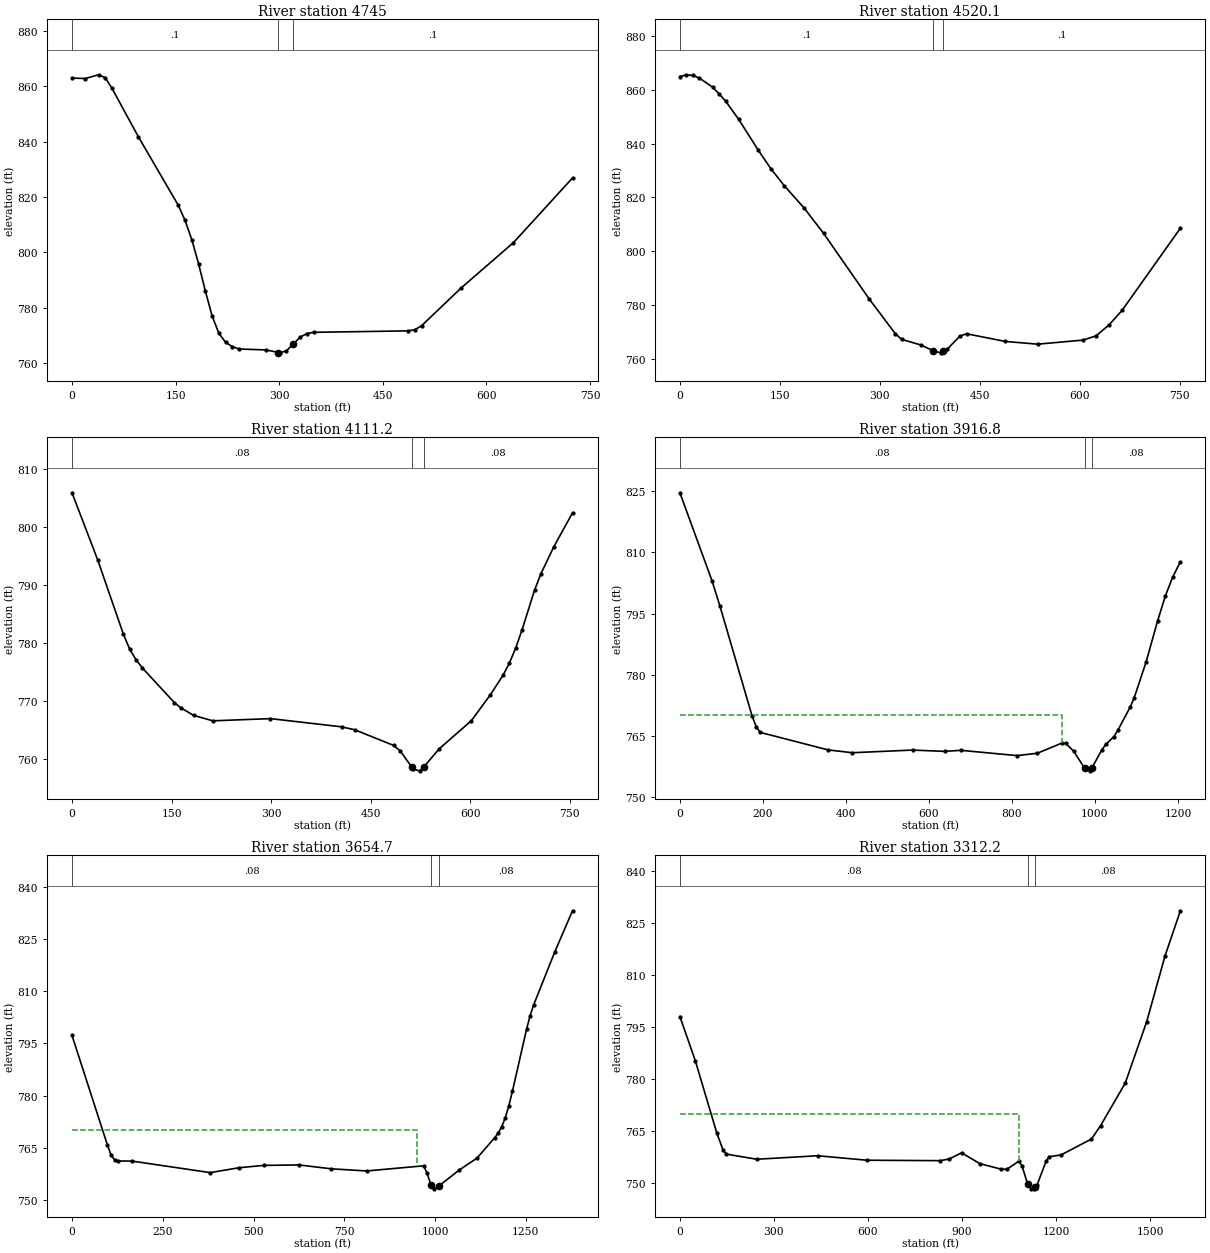
Type RM Length L Ch R = 1 ,4745    ,228.3,224.9,220.1
XS GIS Cut Line= 4
     1667622.142      627348.529     1667556.143      627487.487
      1667582.37      627829.186     1667652.524      628046.229
#Sta/Elev= 30
       0   862.9    19.2  862.75    38.5   864.1    48.1  863.06    57.7  859.29
    96.2  841.67   153.8  817.01   163.6  811.55   173.4  804.62   183.2  795.91
     193  786.06   202.8  777.05   212.6  770.79   222.4  767.49   232.2  765.94
     242  765.09   281.1  764.76   298.9  763.83   300.7  763.71   310.5  764.44
   319.9766.7806   330.1  769.34   339.9  770.68   349.7  771.12   486.8  771.64
   496.5  772.08     506  773.46   563.1  787.07   639.1  803.51   724.6  826.84
#Mann= 3 , 0 , 0
       0      .1       0   298.9    .045       0   319.9      .1       0
Bank Sta=298.9,319.9
XS Rating Curve= 0 ,0
Exp/Cntr=0.3,0.1

Type RM Length L Ch R = 1 ,4520.1  ,408.6,408.9,406.4
XS GIS Cut Line= 3
     1667492.495      627297.581     1667325.771      627551.166
     1667437.373      627984.213
#Sta/Elev= 30
       0  864.81     9.8   865.5    19.6  865.25    29.4  864.24      49  860.92
    58.7  858.44    68.5  855.76    88.1  848.99   117.5  837.54   137.1  830.44
   156.6  824.33     186  816.17   215.4  806.71   283.9  782.35   322.9   769.5
   332.6  767.34   361.8  765.23   379.5763.1406     391  762.34     395762.8855
   400.7  763.66   420.1  768.55   429.9  769.42   488.2  766.56   536.8  765.56
   604.8  767.07   624.3  768.66   643.7   772.7   663.2  778.08   750.7  808.58
#Mann= 3 , 0 , 0
       0      .1       0   379.5    .045       0     395      .1       0
Bank Sta=379.5,395
XS Rating Curve= 0 ,0
Exp/Cntr=0.3,0.1

Type RM Length L Ch R = 1 ,4111.2  ,204.3,194.4,183.4
XS GIS Cut Line= 4
     1667297.612      627442.132     1667095.274      627662.376
     1667161.211       627958.02     1667235.692      628090.891
#Sta/Elev= 30
       0  805.87    38.6  794.33    77.2  781.54    86.8  778.92    96.5  777.05
   106.1  775.64   154.4  769.65     164  768.76   183.3  767.46   212.2  766.52
   299.1   766.9   406.6  765.48   426.1  764.97   484.7  762.28   494.5  761.35
     512758.5543     514  758.21   523.8  757.89     530758.5388   553.1  761.66
     602  766.56   630.6  771.03   649.6  774.38   659.1  776.47   668.6  779.05
   678.2  782.19   697.2   789.1   706.7   791.9   725.8  796.48   754.3  802.41
#Mann= 3 , 0 , 0
       0     .08       0     512    .045       0     530     .08       0
Bank Sta=512,530
XS Rating Curve= 0 ,0
Exp/Cntr=0.3,0.1

Type RM Length L Ch R = 1 ,3916.8  ,253.3,262.1,268.4
XS GIS Cut Line= 5
     1666969.767      627156.938     1666732.424      627509.865
      1666765.02      627700.196     1667103.881      628074.907
     1667096.069      628156.938
#Sta/Elev= 30
       0  824.65    77.3  803.06    96.7  796.76     174  769.83   183.7  767.23
   193.3  765.82   357.6   761.5   415.6  760.82   560.5  761.47   637.8  761.15
   676.7  761.41   812.7  760.11   861.3  760.69   919.6  763.15   929.3  763.11
   948.7  761.22   975.1757.0195   987.6  756.37   993.1  757.14  1016.8  761.54
  1026.5  762.88  1045.9  764.78  1055.6   766.4  1084.8  771.97  1094.5  774.24
  1123.6  783.18  1151.1  793.19  1169.4  799.21  1187.7  804.02    1206  807.71
#Mann= 3 , 0 , 0
       0     .08       0   975.1    .045       0   993.1     .08       0
#XS Ineff= 2 , 0
       0   919.6     770               0
Permanent Ineff=
       F       F
Bank Sta=975.1,993.1
XS Rating Curve= 0 ,0
Exp/Cntr=0.3,0.1

Type RM Length L Ch R = 1 ,3654.7  ,337.6,342.6,340.9
XS GIS Cut Line= 4
     1666785.425       627151.31     1666546.971      627448.102
     1666830.405      628147.059     1666973.807      628343.744
#Sta/Elev= 30
       0   797.3    97.6  765.77   107.4  762.98   117.1  761.53   126.9  761.21
     166  761.17   380.7  757.86   459.1  759.25   527.6  759.94   625.6  760.07
   713.8  758.96   811.7  758.34   968.4  759.82   978.2  757.63   988.6  754.24
   997.8   753.2  1010.6754.0339  1066.4  758.61  1115.4  762.03  1164.2   767.9
  1173.9  769.25  1183.6  771.09  1193.4  773.66  1203.1  777.09  1212.8  781.19
  1251.8  799.04  1261.5  802.92  1271.3  806.06  1329.7  821.35  1378.4  833.14
#Mann= 3 , 0 , 0
       0     .08       0   988.6    .045       0  1010.6     .08       0
#XS Ineff= 2 , 0
       0   948.8     770               0
Permanent Ineff=
       F       F
Bank Sta=988.6,1010.6
XS Rating Curve= 0 ,0
Exp/Cntr=0.3,0.1

Type RM Length L Ch R = 1 ,3312.2  ,382.9,381.4,378.2
XS GIS Cut Line= 5
     1666574.556      626936.695     1666481.585      627051.243
     1666439.528      627840.254       1666505.5      628149.977
     1666532.238      628491.165
#Sta/Elev= 30
       0  798.11    49.2  785.37     118  764.47   137.7  759.68   147.5  758.48
   245.1  756.99   440.2     758   596.2  756.71   830.4  756.58   859.6  757.07
   898.6  758.85   956.8  755.72    1024  754.15  1043.2   754.1  1081.6  756.47
  1091.2  755.09    1109749.9744    1120  748.51  1129.6  748.46    1134748.9435
  1139.2  749.52    1168  756.38  1177.6  757.71    1216  758.24    1313  762.82
  1342.3  766.71  1420.6  778.92    1489  796.61  1547.7  815.63  1596.6   828.6
#Mann= 3 , 0 , 0
       0     .08       0    1109    .045       0    1134     .08       0
#XS Ineff= 2 , 0
       0  1081.6     770               0
Permanent Ineff=
       F       F
Bank Sta=1109,1134
XS Rating Curve= 0 ,0
Exp/Cntr=0.3,0.1

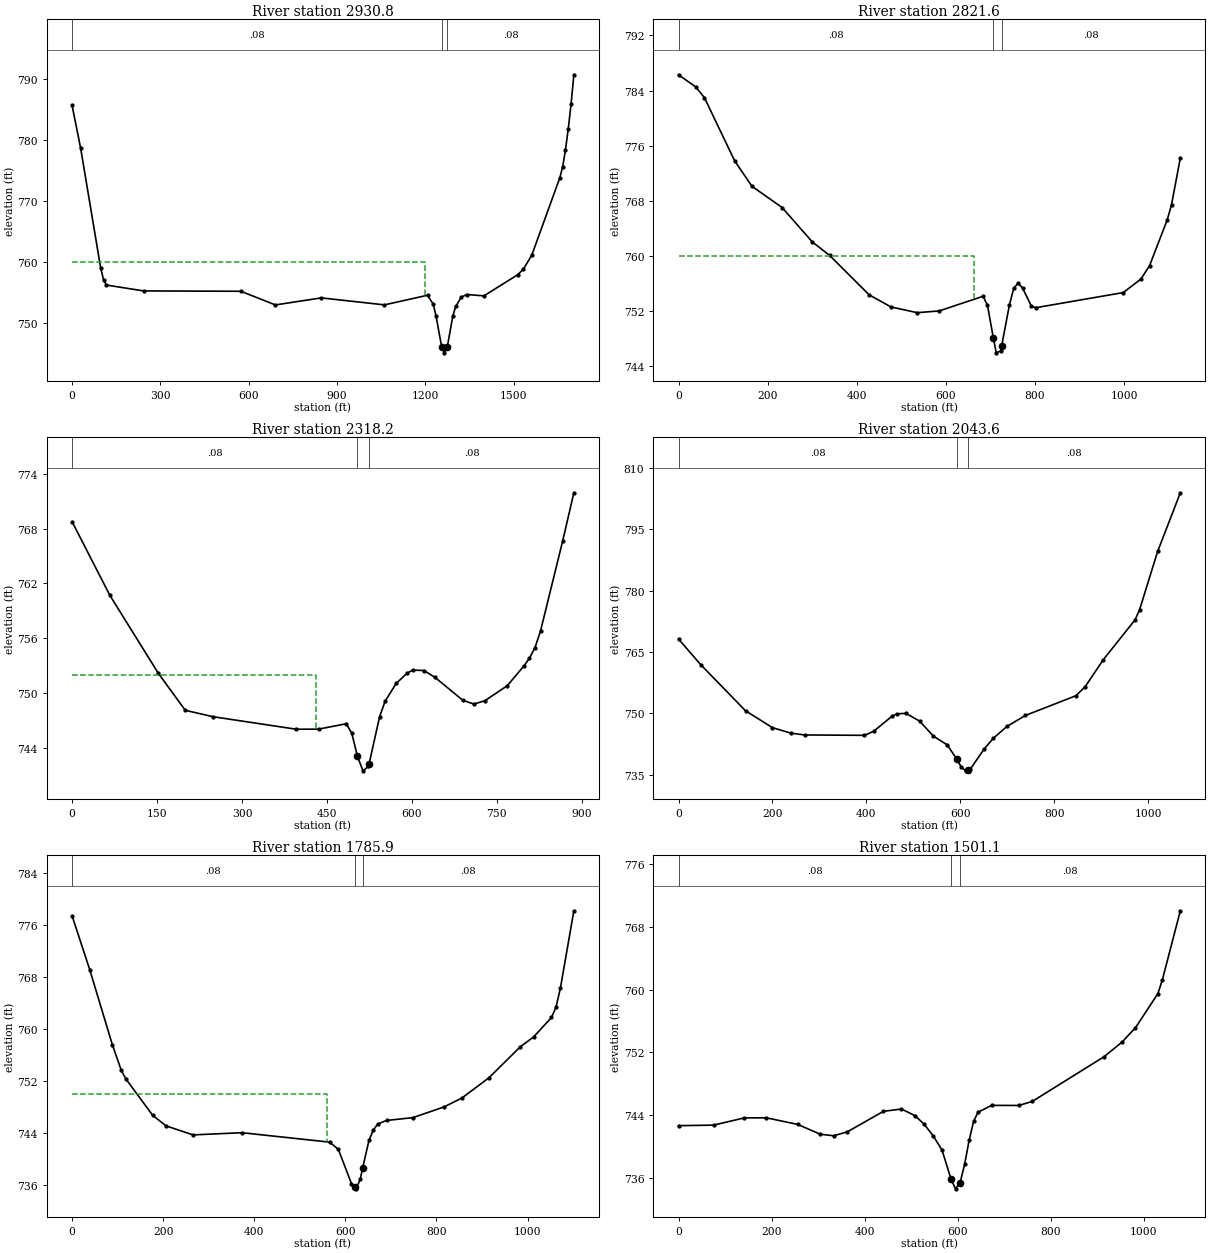
Type RM Length L Ch R = 1 ,2930.8  ,102.7,109.2,113.1
XS GIS Cut Line= 5
       1666449.7      626883.475     1666164.293      627276.289
     1666176.188      627988.107     1666299.334      628279.139
     1666436.679      628411.253
#Sta/Elev= 30
       0  785.63    29.1  778.63    97.1  759.07   106.8  757.14   116.5  756.27
   242.8  755.31   573.3  755.25   690.4  753.02   846.4  754.17  1060.9  753.03
    1207   754.6  1226.2  753.15  1235.8  751.28  1254.9   746.2  1264.5  745.19
  1274.1  746.13  1293.2  751.26  1302.8  752.77    1322  754.31  1341.1  754.72
  1398.6   754.5  1513.5  757.96  1532.5  758.86  1561.1  761.15  1656.4  773.81
  1665.9  775.58  1675.5  778.36    1685   781.8  1694.5  785.83    1704  790.63
#Mann= 3 , 0 , 0
       0     .08       0  1254.9    .045       0  1274.1     .08       0
#XS Ineff= 2 , 0
       0  1197.5     760               0
Permanent Ineff=
       F       F
Bank Sta=1254.9,1274.1
XS Rating Curve= 0 ,0
Exp/Cntr=0.3,0.1

Type RM Length L Ch R = 1 ,2821.6  ,509.2,503.4,494.1
XS GIS Cut Line= 3
     1665724.337      627610.393     1666052.531      627638.161
     1666172.698      628425.789
#Sta/Elev= 30
       0  786.28    38.8  784.51    58.1  782.96   125.9  773.81   164.7  770.12
   232.5  767.03   300.3  762.04   339.2  760.09   427.7  754.38   476.9  752.62
   535.9  751.79   585.1  752.05   683.5  754.17   693.3  752.86   706.3 748.184
     713  745.97   722.8  746.25   725.3  747.03   742.5  752.89   752.3  755.34
   762.2  756.07     772  755.37   791.7  752.76   801.5  752.51   998.2  754.71
  1037.6  756.66  1057.2  758.63  1096.6  765.23  1106.4  767.46  1126.1  774.22
#Mann= 3 , 0 , 0
       0     .08       0   706.3    .045       0   725.3     .08       0
#XS Ineff= 2 , 0
       0   663.8     760               0
Permanent Ineff=
       F       F
Bank Sta=706.3,725.3
XS Rating Curve= 0 ,0
Exp/Cntr=0.3,0.1

Type RM Length L Ch R = 1 ,2318.2  ,262.8,274.6,285
XS GIS Cut Line= 3
     1665610.059      627735.957      1665520.65      627914.776
      1665863.86      628508.994
#Sta/Elev= 30
       0  768.75    66.6  760.71   152.3  752.17   199.9  748.12   248.9  747.42
     396  746.05   435.2  746.06   484.2  746.65     494   745.6   503.8  743.12
   513.6   741.5   523.4  741.98   524.3  742.21     543   747.4   552.8  749.12
   572.4  751.06     592   752.2   601.8  752.52   621.5  752.47   641.1  751.71
   690.1  749.21   709.7   748.8   729.3  749.18   768.5  750.81   797.9  752.97
   807.7  753.82   817.5  754.98   827.3  756.81   866.5  766.68   886.1  771.91
#Mann= 3 , 0 , 0
       0     .08       0   503.8    .045       0   524.3     .08       0
#XS Ineff= 2 , 0
       0     430     752               0
Permanent Ineff=
       F       F
Bank Sta=503.8,524.3
XS Rating Curve= 0 ,0
Exp/Cntr=0.3,0.1

Type RM Length L Ch R = 1 ,2043.6  ,247.4,257.7,266.8
XS GIS Cut Line= 4
     1665561.886      627730.688     1665478.241      627912.163
     1665469.052      628588.099     1665560.981      628757.412
#Sta/Elev= 30
       0  768.18    47.6  761.87   142.7  750.63   199.8  746.52     239  745.18
   268.4  744.73   395.8  744.63   415.4  745.61   454.6  749.31   464.4  749.88
   483.9  750.01   513.3  748.12   542.7  744.44   572.1   742.3     592738.8806
   601.5     737   611.3  735.95   616.5736.1594   621.1  736.35   650.5  741.25
   670.1   743.9   699.5  746.83   738.7   749.5   846.4  754.33     866  756.55
   904.7  763.17   972.2  772.89   981.8  775.38  1020.3  789.64  1068.5  803.95
#Mann= 3 , 0 , 0
       0     .08       0     592    .045       0   616.5     .08       0
Bank Sta=592,616.5
XS Rating Curve= 0 ,0
Exp/Cntr=0.3,0.1

Type RM Length L Ch R = 1 ,1785.9  ,312.5,284.8,255.8
XS GIS Cut Line= 4
     1665426.028      627690.434     1665382.744       628022.05
     1665219.437      628402.208     1665343.563      628733.186
#Sta/Elev= 30
       0  777.38    39.3     769    88.5  757.57   108.2  753.63     118  752.35
     177  746.74   206.6  745.12   265.6  743.74   372.9  744.08   565.4  742.63
   584.6  741.52   613.5  736.25   620.1 735.705   623.1  735.46   632.7   736.9
   638.1738.7281     652  742.93   661.6  744.52   671.2  745.41   690.4  745.96
   748.2  746.39   816.9  748.04   856.2  749.42   915.1   752.5   983.8  757.25
  1013.3  758.78  1052.6  761.77  1062.4  763.33  1072.2  766.29  1101.7  778.15
#Mann= 3 , 0 , 0
       0     .08       0   620.1    .045       0   638.1     .08       0
#XS Ineff= 2 , 0
       0     560     750               0
Permanent Ineff=
       F       F
Bank Sta=620.1,638.1
XS Rating Curve= 0 ,0
Exp/Cntr=0.3,0.1

Type RM Length L Ch R = 1 ,1501.1  ,266.6,267.8,268.1
XS GIS Cut Line= 4
     1664632.439      627884.338     1664717.765      628062.993
     1665173.684      628468.974     1665272.396      628719.974
#Sta/Elev= 30
       0  742.69    75.4  742.76   141.4  743.68   188.6  743.69   256.1  742.85
   304.6   741.6   333.6  741.41   362.7  741.91   440.2  744.51     479  744.81
   508.1  743.96   527.4   742.9   546.8  741.43   566.2  739.58   585.6  735.88
   595.3  734.66     605  735.43   614.7  737.78   624.4  740.82     634  743.24
   643.7  744.41   672.8  745.27   730.9  745.26     760  745.77   914.4  751.46
     953  753.32   981.8  755.14    1030  759.48  1039.6  761.23  1078.2  770.01
#Mann= 3 , 0 , 0
       0     .08       0   585.6    .045       0     605     .08       0
Bank Sta=585.6,605
XS Rating Curve= 0 ,0
Exp/Cntr=0.3,0.1

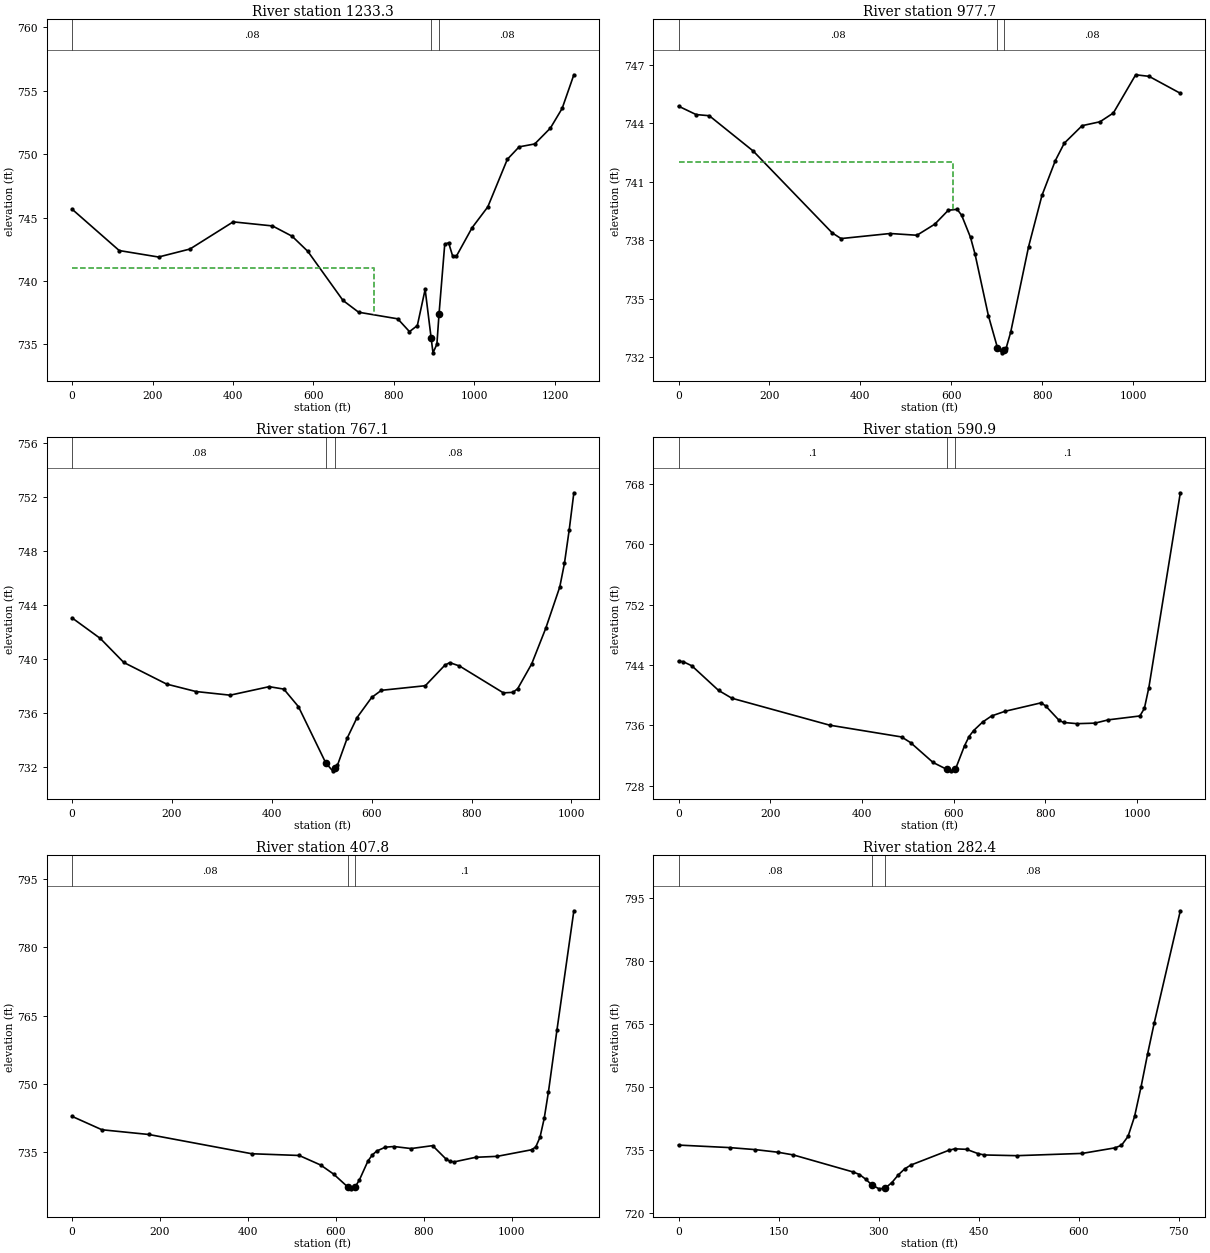
Type RM Length L Ch R = 1 ,1233.3  ,251,255.6,258.3
XS GIS Cut Line= 3
     1664591.498      627742.571     1664597.107      628269.937
     1665112.766      628772.049
#Sta/Elev= 30
       0  745.66   117.2   742.4   214.9  741.89     293  742.52   400.4  744.66
   498.1  744.34   546.8  743.53   585.8  742.34   673.3  738.47   712.2  737.54
   809.4  737.02   838.6  736.01   858.1  736.49   877.5  739.34   892.4  735.51
     897  734.34   906.7  735.02     912   737.4   926.2   742.9   935.9  743.01
   945.6  741.99   955.4  741.97   994.2   744.2  1033.2  745.84  1081.8  749.59
    1111  750.57  1149.9   750.8  1188.8  752.05    1218   753.6  1247.1  756.25
#Mann= 3 , 0 , 0
       0     .08       0   892.4    .045       0     912     .08       0
#XS Ineff= 2 , 0
       0     750     741               0
Permanent Ineff=
       F       F
Bank Sta=892.4,912
XS Rating Curve= 0 ,0
Exp/Cntr=0.3,0.1

Type RM Length L Ch R = 1 ,977.7   ,202.2,210.6,218.6
XS GIS Cut Line= 3
     1664314.487      627982.051     1664416.454      628314.492
     1664880.822      628910.985
#Sta/Elev= 30
       0  744.87    38.6  744.44    67.6  744.38   164.2  742.57   338.1  738.37
   357.5  738.08   465.5  738.34   524.4  738.25   563.7  738.82   593.2  739.53
   612.8  739.58   622.6  739.28   642.2  738.14   652.1  737.29   681.5  734.13
   701.5  732.48     711  732.22   716.5  732.37   720.8  732.48   730.6  733.28
   769.9  737.66   799.3  740.29   828.8  742.08   848.4  742.97   887.7  743.87
     927  744.07   956.4  744.52  1005.5  746.48  1034.9   746.4  1103.7  745.53
#Mann= 3 , 0 , 0
       0     .08       0   701.5    .045       0   716.5     .08       0
#XS Ineff= 2 , 0
       0     603     742               0
Permanent Ineff=
       F       F
Bank Sta=701.5,716.5
XS Rating Curve= 0 ,0
Exp/Cntr=0.3,0.1

Type RM Length L Ch R = 1 ,767.1   ,173.8,176.2,178.3
XS GIS Cut Line= 4
     1664341.006      628179.012     1664341.424      628339.142
     1664552.115      629020.705       1664629.2      629126.929
#Sta/Elev= 30
       0  743.07    56.5  741.55   103.6  739.77   189.4  738.17   248.1  737.62
   316.5  737.35   394.7  737.98     424   737.8   453.3   736.5   507.9732.3452
   521.7  731.75   526.9  731.97   531.5  732.17     551  734.18   570.6  735.69
   599.9  737.18   619.4  737.71   707.4  738.05   746.5  739.57   756.2  739.76
   775.8  739.51   863.7  737.52   882.9  737.56   892.3  737.83   920.4  739.67
   948.5   742.3   976.6  745.36     986  747.12   995.4  749.56  1004.8  752.33
#Mann= 3 , 0 , 0
       0     .08       0   507.9    .045       0   526.9     .08       0
Bank Sta=507.9,526.9
XS Rating Curve= 0 ,0
Exp/Cntr=0.3,0.1

Type RM Length L Ch R = 1 ,590.9   ,174.8,183.2,189.6
XS GIS Cut Line= 4
       1664262.2      628164.031     1664245.194      628512.562
     1664333.568      628945.242     1664411.505      629238.683
#Sta/Elev= 30
       0  744.48     9.7  744.47    29.1   743.9    87.2  740.65   116.3  739.61
   329.6  736.04   486.3  734.48     506  733.73     555   731.1   584.5   730.2
   594.3  729.99     602730.1942   604.1  730.25   623.7  733.32   633.5  734.53
   643.4  735.32     663  736.45   682.6  737.26     712  737.88   790.6     739
   800.4   738.6   829.7  736.69   839.5   736.4   868.9  736.24   908.1  736.31
   937.5  736.75    1006  737.26  1015.8  738.26  1025.6  741.03  1094.2  766.83
#Mann= 3 , 0 , 0
       0      .1       0   584.5    .045       0     602      .1       0
Bank Sta=584.5,602
XS Rating Curve= 0 ,0
Exp/Cntr=0.3,0.1

Type RM Length L Ch R = 1 ,407.8   ,130.6,125.4,121
XS GIS Cut Line= 4
     1664157.165      628151.588     1664149.151      628413.291
     1664105.577      629175.474     1664082.512      629288.741
#Sta/Elev= 30
       0  742.88    67.9  739.94   174.6   738.9   408.6  734.67   516.3  734.29
   565.2  732.19   594.6   730.2   627.5727.3071   633.8  726.96   643.5  727.38
   653.3  728.93   672.9  733.12   682.7  734.41   692.5  735.26     712  736.11
   731.6  736.26   770.8  735.81   819.7  736.45   849.1  733.61   858.9     733
   868.6  732.88   917.6  733.89   966.5   734.1  1044.5  735.54  1054.2  736.17
  1063.8  738.29  1073.4  742.44    1083  748.26  1102.3  761.81  1140.8  788.05
#Mann= 3 , 0 , 0
       0     .08       0   627.5    .045       0   643.5      .1       0
Bank Sta=627.5,643.5
XS Rating Curve= 0 ,0
Exp/Cntr=0.3,0.1

Type RM Length L Ch R = 1 ,282.4   ,105.1,105.2,104.8
XS GIS Cut Line= 6
      1664020.91      628536.651     1664004.634      628650.584
     1664002.724      628707.788     1664017.308      628939.733
     1663996.474      629069.594     1664028.072      629282.962
#Sta/Elev= 30
       0  736.26    76.9  735.66   115.1  735.18     149  734.56   172.3  733.91
   261.5  729.87   271.3  729.26   281.1  728.08   289.5726.8286   300.6  725.85
     310  726.03   319.9  727.35   329.4  729.15   338.9  730.58   348.2   731.5
   404.9     735   413.9  735.37   431.8  735.25   449.7  734.19   458.7  733.91
   507.2  733.74   605.3  734.28   654.3   735.6   664.1  736.21   673.9  738.32
   683.7  743.07   693.5  750.17   703.3  757.99   713.1  765.26   752.3     792
#Mann= 3 , 0 , 0
       0     .08       0   289.5    .045       0     310     .08       0
Bank Sta=289.5,310
XS Rating Curve= 0 ,0
Exp/Cntr=0.3,0.1