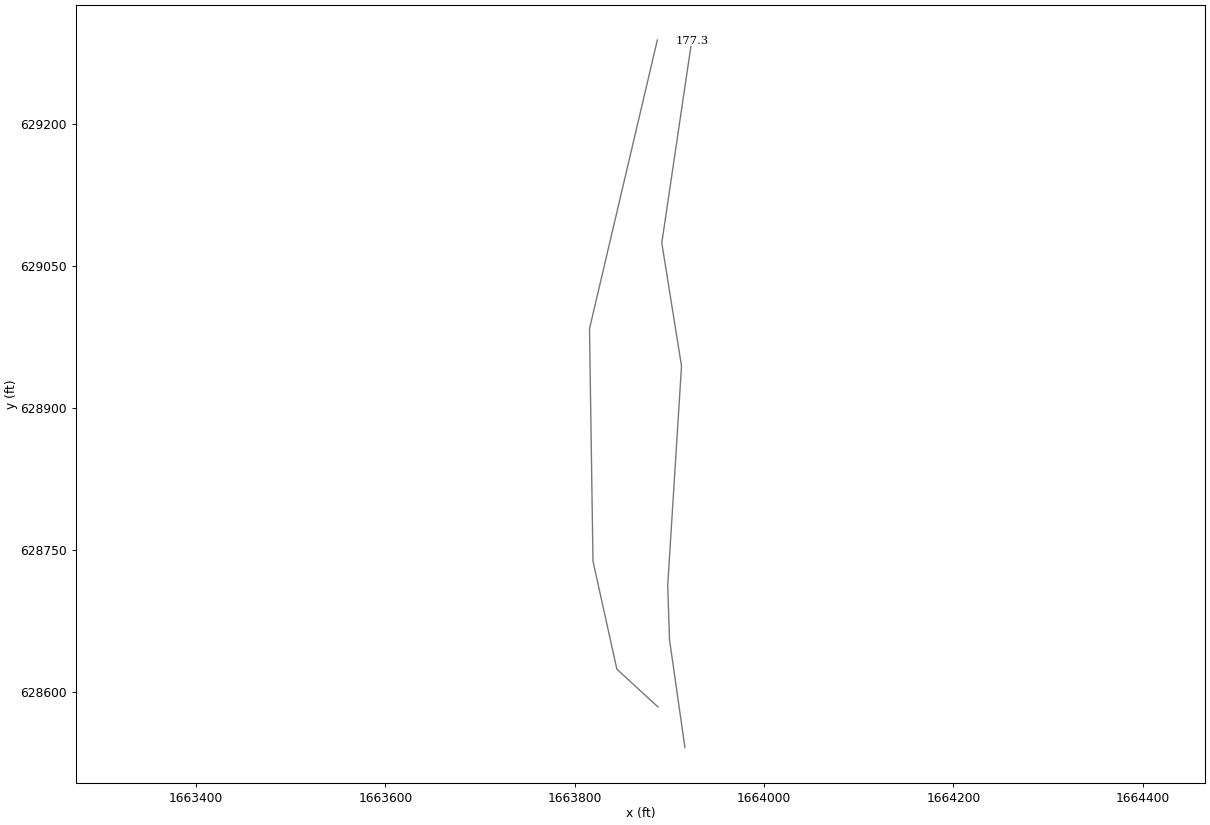
HEC-RAS study MNGORN.prj: MNGORN

--- MNGORN.g01 (geometry) --- (continued)

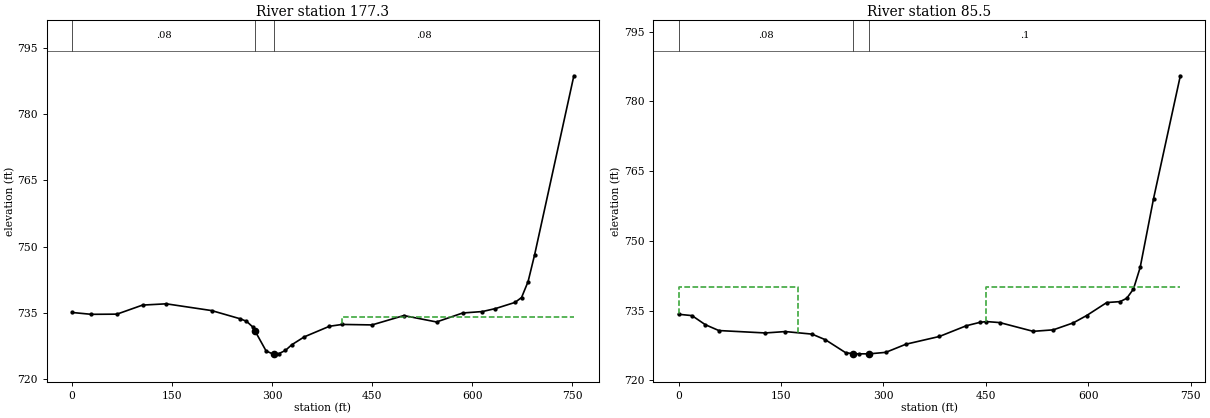
Type RM Length L Ch R = 1 ,177.3   ,89,91.8,94
XS GIS Cut Line= 6
     1663916.396      628541.165      1663900.12      628655.097
     1663898.211      628712.302     1663912.794      628944.247
     1663891.961      629074.108     1663923.558      629287.476
#Sta/Elev= 30
       0  735.07    28.8  734.65    67.3  734.69   105.6  736.74   141.2  737.03
   209.2   735.5   251.8  733.65   261.5  733.08   271.3  731.73     274730.9613
   290.9  726.35   300.6   725.7   303.4725.7221   310.4  725.77   319.9  726.48
   329.4  727.76   348.2  729.55   385.8  731.94   404.9  732.36   449.7  732.25
   497.4  734.37   546.4  732.92   585.6  734.95   615.1  735.28   634.7  735.95
   664.1  737.35   673.9  738.46   683.7  742.08   693.5  748.16   752.3  788.68
#Mann= 3 , 0 , 0
       0     .08       0     274    .045       0   303.4     .08       0
#XS Ineff= 2 , 0
       0                   404.9       0     734
Permanent Ineff=
       F       F
Bank Sta=274,303.4
XS Rating Curve= 0 ,0
Exp/Cntr=0.3,0.1

Type RM Length L Ch R = 1 ,85.5    ,97.8,85.5,72.9
XS GIS Cut Line= 5
     1663887.924      628584.047     1663844.521      628623.978
     1663819.305      628738.011     1663815.614      628983.536
     1663887.273      629288.474
#Sta/Elev= 30
       0  734.21    19.7  733.92    39.3  731.96      59  730.71   127.1  730.19
   156.3  730.49   195.4  729.94     215  728.73   244.5  725.96   255.8725.7173
   264.2   725.7   279.3   725.7   303.4  726.02   332.9  727.77     382  729.44
   421.3  731.74   440.9  732.46   450.7  732.64   470.3  732.42   519.2  730.54
   548.6  730.86   577.9  732.36   597.5  733.94   626.9  736.73   646.5  736.93
   656.2  737.65     666  739.64   675.8  744.27   695.4  759.08   734.6  785.49
#Mann= 3 , 0 , 0
       0     .08       0   255.8    .045       0   279.3      .1       0
#XS Ineff= 2 , 0
       0     175     740   450.7       0     740
Permanent Ineff=
       F       F
Bank Sta=255.8,279.3
XS Rating Curve= 0 ,0
Exp/Cntr=0.3,0.1

Chan Stop Cuts=-1
Use User Specified Reach Order=0
Composite Channel Slope=5